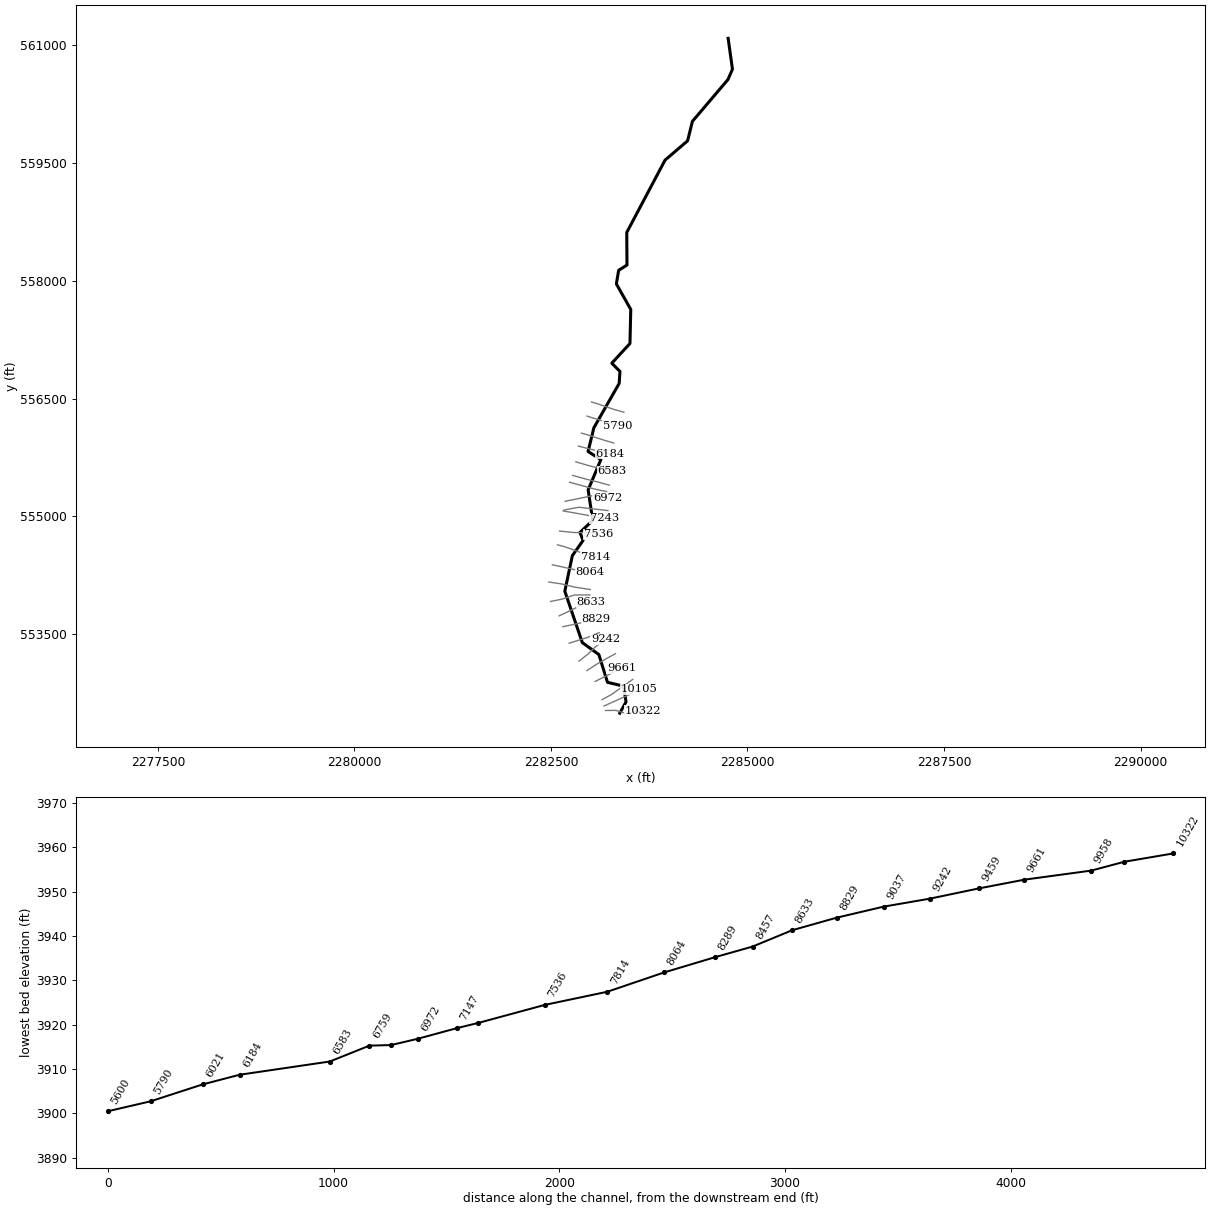
--- FIRSTFK.prj (project) ---

Proj Title=FIRSTFK
Current Plan=p01
Default Exp/Contr=0,0
English Units
Geom File=g01
Flow File=f01
Plan File=p01
Background Map Layer=Inundation Boundary (01pct Value_0)
BEGIN DESCRIPTION:
----------MODEL BY WOOD PLC 2021----------
Stream Name: First Fork
Flood Zone: Approximate
Pocahontas County, WV
HEC-RAS Version: RAS 6.1
Vertical Datum: NAVD88
Projection: NAD 1983 StatePlane West Virginia S FIPS 4702 (US Feet)
Terrain: 1-meter LIDAR (FEMA Region III 3DEP collected 2016-2018)
Land Use: 2019 NLCD
Hydrologic Method:
WV 2010 Regional Regression Equations
Model Notes:
Model extends beyond county boundary on the downstream end into Randolpf county, Tie in at XS 13188
END DESCRIPTION:
DSS File=dss
DSS Export Rating Curves= 0
DSS Export Rating Curve Sorted= 0
DSS Export Volume Flow Curves= 0
DXF OffsetX= 0
DXF OffsetY= 0
DXF ScaleX= 0
DXF ScaleY= 0

--- FIRSTFK.p01 (plan) ---

Plan Title=Floodplain
Program Version=6.10
Short Identifier=Floodplain
Geom File=g01
Flow File=f01
Subcritical Flow
K Sum by GR= 0
Std Step Tol= 0.01
Critical Tol= 0.01
Num of Std Step Trials= 20
Max Error Tol= 0.3
Flow Tol Ratio= 0.001
Split Flow NTrial= 30
Split Flow Tol= 0.02
Split Flow Ratio= 0.02
Log Output Level= 0
Friction Slope Method= 1
Unsteady Friction Slope Method= 2
Unsteady Bridges Friction Slope Method= 1
Parabolic Critical Depth
Global Vel Dist= 0 , 0 , 0
Global Log Level= 0
CheckData=True
Encroach Param=-1 ,0,0, 0
Computation Interval=0.1SEC
Output Interval=1SEC
Instantaneous Interval=Max Profile
Mapping Interval=1HOUR
Computation Time Step Use Courant=        0
Computation Time Step Use Time Series=    0
Computation Time Step Count To Double=0
Computation Time Step Max Doubling=0
Computation Time Step Max Halving=0
Computation Time Step Residence Courant=0
Run HTab= 0
Run UNet= 0
Run Sediment= 0
Run PostProcess= 0
Run WQNet= 0
Run RASMapper=-1
UNET Theta= 0
UNET Theta Warmup= 0
UNET ZTol= 0
UNET ZSATol= 0
UNET MxIter= 0
UNET Max Iter WO Improvement= 0
UNET MaxInSteps= 0
UNET DtIC= 0
UNET DtMin= 0
UNET MaxCRTS= 0
UNET WFStab= 0
UNET SFStab= 0
UNET WFX= 1
UNET SFX= 1
UNET Gravity=32.174
UNET 1D Methodology=Finite Difference
UNET DSS MLevel= 1
UNET Pardiso=0
UNET DZMax Abort= 0
UNET Use Existing IB Tables= 0
UNET Froude Reduction=False
UNET Froude Limit= 0
UNET Froude Power= 0
UNET D1 Cores= 0
UNET WindReference=Eulerian
UNET WindDragFormulation=Hsu (1988)
UNET D2 Coriolis=0
UNET D2 Cores= 0
UNET D2 Theta= 1
UNET D2 Theta Warmup= 1
UNET D2 Z Tol= 0.01
UNET D2 Volume Tol= 0.01
UNET D2 Max Iterations= 20
UNET D2 Equation= 0
UNET D2 RampUpFraction=0.1
UNET D2 TimeSlices= 1
UNET D2 Turbulence Formulation=Non-Conservative (original)
UNET D2 Eddy Viscosity=0.3
UNET D2 Transverse Eddy Viscosity=0.3
UNET D2 Smagorinsky Mixing=0
UNET D2 BCVolumeCheck=0
UNET D2 Cores=0
UNET D2 SolverType=PARDISO (Direct)
UNET D2 Minimum Iterations= 2147483647
UNET D2 Maximum Iterations= 2147483647
UNET D2 Restart Number= 10
UNET D2 Relaxation Coeff=1.3
UNET D2 SOR Precondition Iterations= 10
UNET D2 ILUT Maximum Fill= 8
UNET D2 ILUT Tolerance=1E-08
UNET D1D2 MaxIter= 0
UNET D1D2 ZTol=0.01
UNET D1D2 QTol=0.1
UNET D1D2 MinQTol=1
DSS File=dss
Write IC File= 0
Write IC File at Fixed DateTime=0
Write IC File at Sim End=0
Echo Input=False
Echo Parameters=False
Echo Output=False
Write Detailed= 0
HDF Write Warmup=0
HDF Write Time Slices=0
HDF Flush=0
HDF Compression= 1
HDF Chunk Size= 1
HDF Spatial Parts= 1
HDF Use Max Rows=0
HDF Fixed Rows= 1
Calibration Method= 0
Calibration Iterations= 20
Calibration Max Change=0.05
Calibration Tolerance=0.2
Calibration Maximum=1.5
Calibration Minimum=0.5
Calibration Optimization Method= 1
WQ AD Non Conservative
WQ ULTIMATE=-1
WQ Max Comp Step=1HOUR
WQ Output Interval=15MIN
WQ Output Selected Increments= 0
WQ Output face flow=0
WQ Output face velocity=0
WQ Output face area=0
WQ Output face dispersion=0
WQ Output cell volume=0
WQ Output cell surface area=0
WQ Output cell continuity=0
WQ Output cumulative cell continuity=0
WQ Output face conc=0
WQ Output face dconc_dx=0
WQ Output face courant=0
WQ Output face peclet=0
WQ Output face adv mass=0
WQ Output face disp mass=0
WQ Output cell mass=0
WQ Output cell source sink temp=0
WQ Output nsm pathways=0
WQ Output nsm derived pathways=0
WQ Create Restart=0
WQ Fixed Restart=0
WQ System Summary=0
WQ Write To DSS=0
Sorting and Armoring Iterations= 10
XS Update Threshold= 0.02
Bed Roughness Predictor= 0
Hydraulics Update Threshold= 0.02
Energy Slope Method= 1
Volume Change Method= 1
Sediment Retention Method= 0
Sediment TS Multiplier= 1
Warm Up Method= 0
XS Weighting Method= 0
Number of US Weighted Cross Sections= 1
Number of DS Weighted Cross Sections= 1
Upstream XS Weight=0
Main XS Weight=1
Downstream XS Weight=0
Number of DS XS's Weighted with US Boundary= 1
Upstream Boundary Weight= 1
Weight of XSs Associated with US Boundary= 0
Number of US XS's Weighted with DS Boundary= 1
Downstream Boundary Weight= 0.5
Weight of XSs Associated with DS Boundary= 0.5
Percentile Method= 0
Sediment Output Level= 3
Mass or Volume Output= 0
Output Increment Type= 1
Profile and TS Output Increment= 1
Transport Output Increment 1
XS Output Flag= 0
XS Output Increment= 10
Read HDF5 Sediment Hotstart= 0
Sediment Hotstart Type= 0
Write Gradation File= 0
Read Gradation Hotstart= 0
Write HDF5 File= 1
Write Binary Output= 1
Write DSS Sediment File= 0
DSS Sediment Output Type= 1
SV Curve= 0
Specific Gage Flag= 0
Subcell Erosion Methods= 0
Subcell Deposition Methods= 0
Advection Scheme= 1
Matrix Solver= 0
Implicit Weighting Factor= 1
Maximum Outer Loop Convergence Iterations= 5
Convergence Maximum Absolute= 0.001
Convergence RMSE= 0.0001
Grain Fractions Max Abs Error= 0.001
Max Subgrid Regions= 1
Max Subgrid Length Scale= 3.402823E+38
Initial Layer Thickness= 3.402823E+38
Min Layer Thickness= 3.402823E+38
Max Layer Thickness= 3.402823E+38
Number of Layers= 5

--- FIRSTFK.f01 (steady flow) ---

Flow Title=Flow
Program Version=6.10
Number of Profiles= 6
Profile Names=01pct,10pct,04pct,02pct,0_2pct,01plus
River Rch & RM=FIRSTFK,Main            ,10322
     660     351     465     560     920     977
River Rch & RM=FIRSTFK,Main            ,6583
     771     412     545     655    1070    1140
River Rch & RM=FIRSTFK,Main            ,2969
     940     506     667     799    1300    1390
River Rch & RM=FIRSTFK,Main            ,2107
    1170     638     837    1000    1620    1740
Boundary for River Rch & Prof#=FIRSTFK,Main            , 1
Up Type= 0
Dn Type= 1
Dn Known WS=3796.7
Boundary for River Rch & Prof#=FIRSTFK,Main            , 2
Up Type= 0
Dn Type= 1
Dn Known WS=3796
Boundary for River Rch & Prof#=FIRSTFK,Main            , 3
Up Type= 0
Dn Type= 1
Dn Known WS=3796.3
Boundary for River Rch & Prof#=FIRSTFK,Main            , 4
Up Type= 0
Dn Type= 1
Dn Known WS=3796.5
Boundary for River Rch & Prof#=FIRSTFK,Main            , 5
Up Type= 0
Dn Type= 1
Dn Known WS=3797.2
Boundary for River Rch & Prof#=FIRSTFK,Main            , 6
Up Type= 0
Dn Type= 1
Dn Known WS=3797.4
DSS Import GetInterval= 0
DSS Import GetPeak= 0
DSS Import FillOption= 0

--- FIRSTFK.g01 (geometry) ---

Geom Title=Geometry
Program Version=6.10

River Reach=FIRSTFK         ,Main
Reach XY= 30
2283375.82300003552496.5900000042283455.77377267552640.998020291
2283424.08700003552840.7870000152283220.00300002552889.072999999
2283109.77899998553242.5069999992282899.20900002553395.012000009
2282676.86900003      554048.8312282772.93199486554501.222320303
2282909.46771581554695.477223635 2282869.6613832 554796.18724525
2283032.07122038554949.441625953      2282973.72555338.405000001
2283135.96574861 555723.674795972282972.68000002555825.881999999
2283046.57900003556128.2469999942283368.43473125556692.560932651
2283378.58699998556844.774000004     2283274.587      556949.919
2283505.59400003557200.1439999942283515.84200001557633.395000011
     2283332.537557958.7700000112283361.98800004558132.015000016
2283467.55249955 558198.434496792283464.81800002558613.604000017
2283951.99556792559533.936957195  2284238.601163559779.143966302
2284300.06200001560027.0460000042284752.26800004560559.187999994
2284809.34662078560690.8962432152284754.42003363561083.337543637

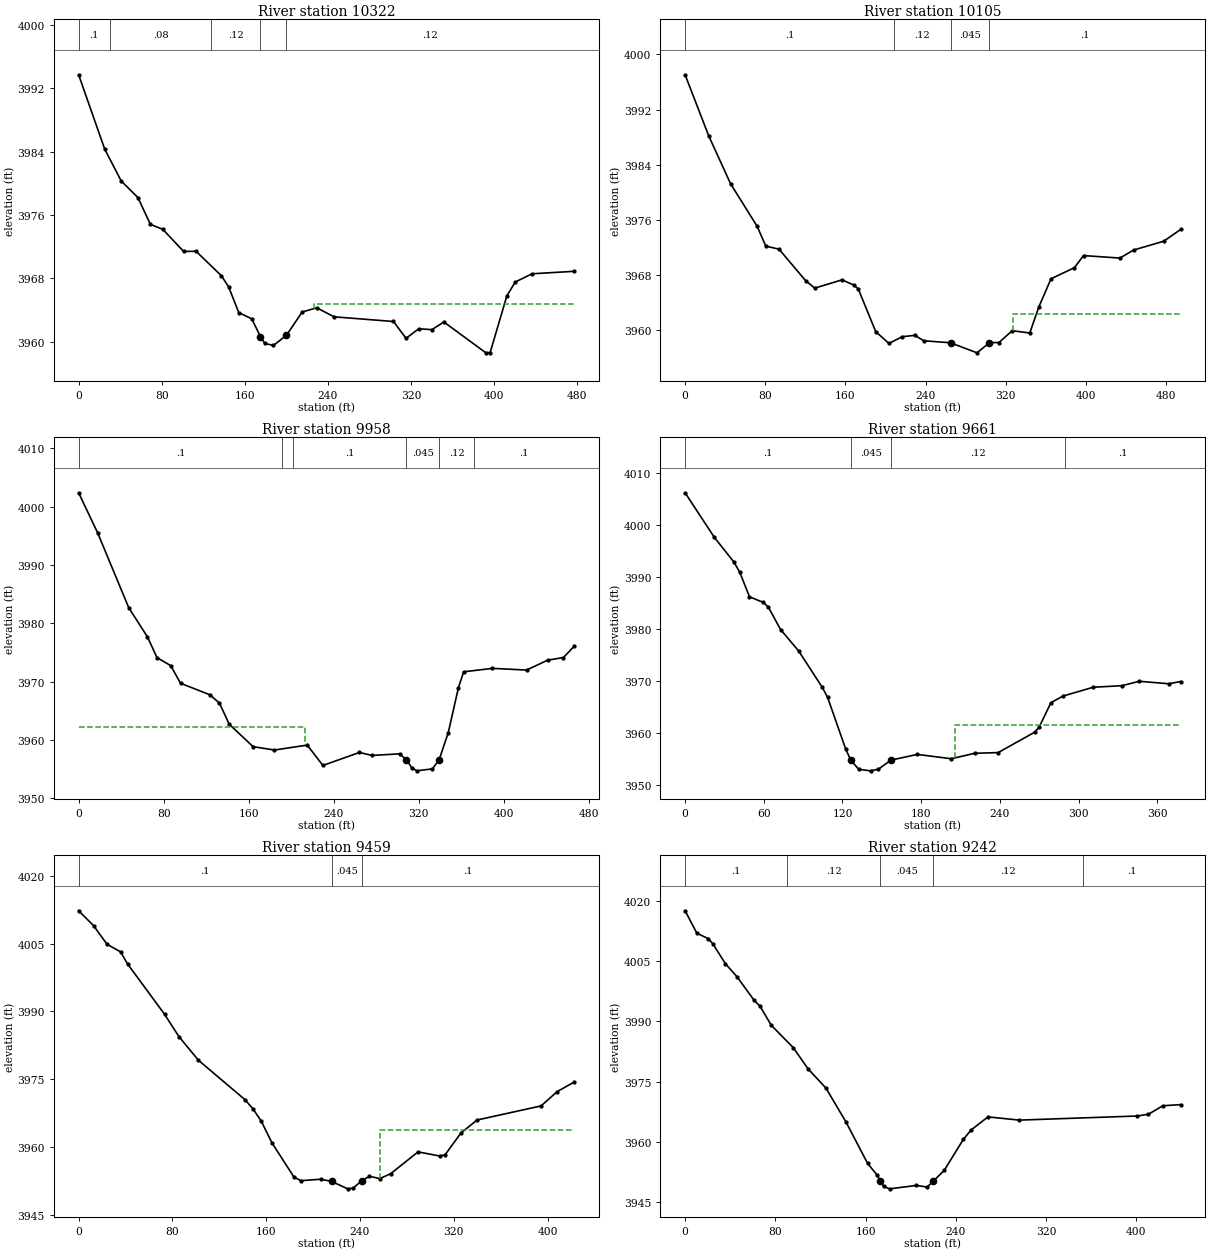
Type RM Length L Ch R = 1 ,10322   ,193.3,217.4,229.1
XS GIS Cut Line= 4
2283195.08690843552530.6303049312283323.01956979552532.660982095
2283452.98290832552494.0781159692283664.17333344552526.568950602
#Sta/Elev= 30
       0 3993.72    25.1 3984.33    41.1 3980.28    57.1 3978.21    69.1 3974.82
    81.1 3974.19   101.1  3971.4   113.1 3971.42   137.5 3968.33   144.5 3966.91
   154.2 3963.68   166.7 3962.89   175.1 3960.64   179.2 3959.78   187.6 3959.53
   200.1  3960.8   215.3 3963.75   229.3 3964.28     246 3963.14   303.2 3962.55
   315.3 3960.42   327.5 3961.63   340.2 3961.52   351.7 3962.49   392.2 3958.59
   396.3 3958.63   412.4  3965.8   420.5 3967.54   436.7 3968.58   477.2 3968.89
#Mann= 5 ,-1,0
       0      .1       0      30     .08       0  127.95     .12       0
   175.1    .045       0   200.1     .12       0
#XS Ineff= 2 , 0
                          226.82         3964.76
Permanent Ineff=
       F       F
Bank Sta=175.1,200.1
XS Rating Curve= 0 ,0
Exp/Cntr(USF)=0,0
Exp/Cntr=0.3,0.1

Type RM Length L Ch R = 1 ,10105   ,144.9,146.6,148.9
XS GIS Cut Line= 4
2283174.78013678552587.4892655382283318.95821546552652.470934804
 2283511.8725461552739.7900528792283621.52911298552798.679690651
#Sta/Elev= 30
       0 3997.05    23.6 3988.18    45.4 3981.23    71.9 3975.07    80.5 3972.19
    93.7 3971.75   120.3 3967.17   129.4  3966.1   156.6  3967.3   168.3 3966.54
   172.7    3966   190.2 3959.79   203.4 3958.07   216.6 3959.05   229.1 3959.25
   238.2 3958.46   264.9 3958.17   291.2 3956.71   303.73958.184   313.2 3958.21
   326.3 3959.92   343.9 3959.59   352.7 3963.29   365.1 3967.46   388.4 3969.06
   397.5 3970.82   433.8 3970.46   447.4 3971.62   477.5  3972.9   494.4 3974.61
#Mann= 4 ,-1,0
       0      .1       0  208.15     .12       0   264.9    .045       0
   303.7      .1       0
#XS Ineff= 2 , 0
                          326.74         3962.28
Permanent Ineff=
       F       F
Bank Sta=264.9,303.7
XS Rating Curve= 0 ,0
Exp/Cntr(USF)=0,0
Exp/Cntr=0.3,0.1

Type RM Length L Ch R = 1 ,9958    ,296.5,296.9,289.5
XS GIS Cut Line= 4
2283152.44268797 552668.716352122283276.31399501552737.759375715
2283479.38171146552881.937454397 2283540.3020264552926.612352017
#Sta/Elev= 30
       0 4002.37    17.8 3995.54    47.2 3982.66    64.8 3977.67    73.7 3974.14
    86.7 3972.74    95.9 3969.73   123.3 3967.77   132.5 3966.34   141.7 3962.72
   164.2 3958.86   184.3 3958.29   215.2 3959.13   229.9 3955.64   264.3 3957.87
   276.1 3957.36     302 3957.63   308.4 3956.66   313.4 3955.28   318.2 3954.72
     333 3955.06   339.43956.662   347.9 3961.27   357.5    3969   362.4 3971.69
   389.5 3972.28   421.6 3971.99   441.4 3973.68   456.3 3974.14   466.4 3976.06
#Mann= 6 ,-1,0
       0      .1       0  191.81     .12       0  201.81      .1       0
   308.4    .045       0   339.4     .12       0  371.81      .1       0
#XS Ineff= 2 , 0
          213.52 3962.16
Permanent Ineff=
       F       F
Bank Sta=308.4,339.4
XS Rating Curve= 0 ,0
Exp/Cntr(USF)=0,0
Exp/Cntr=0.3,0.1

Type RM Length L Ch R = 1 ,9661    ,198.9,202.5,199.7
XS GIS Cut Line= 4
2283063.09289273552900.2135488782283146.35065648552942.857769334
2283312.86618397 553026.115533082283400.18530205  553070.7904307
#Sta/Elev= 30
       0 4006.18    22.3  3997.6    37.2 3992.85    41.7 3990.87    49.1 3986.16
    59.6 3985.09    63.5 3984.16    72.8 3979.86    86.6 3975.73   104.5 3968.77
   108.6 3966.84   122.4 3956.89   126.33954.725   132.4 3952.96   141.4 3952.67
   147.3 3952.98     1573954.739   177.1 3955.83   202.9    3955   220.8 3956.05
   238.7 3956.18   266.6 3960.12     270 3961.12   278.9 3965.78   287.9 3967.04
   311.2 3968.76   332.9 3969.05   346.3  3969.9   368.8 3969.43   377.8 3969.86
#Mann= 4 ,-1,0
       0      .1       0   126.3    .045       0     157     .12       0
  289.71      .1       0
#XS Ineff= 2 , 0
                           205.5          3961.4
Permanent Ineff=
       F       F
Bank Sta=126.3,157
XS Rating Curve= 0 ,0
Exp/Cntr(USF)=0,0
Exp/Cntr=0.3,0.1

Type RM Length L Ch R = 1 ,9459    ,207.5,216.6,211.5
XS GIS Cut Line= 4
2282957.49768017553038.2995960672283075.27695572 553115.46532832
2283223.51638873553200.7537692312283320.98889263553253.551375509
#Sta/Elev= 30
       0 4012.25    12.7 4008.97    24.2 4004.84    35.8 4003.15    41.7 4000.49
    73.4  3989.3    85.5 3984.41   102.2 3979.16   141.8 3970.45   148.6 3968.43
   155.7 3965.72   164.9 3960.87   183.7 3953.29   189.6 3952.49   206.4 3952.82
   215.7 3952.35   229.5 3950.69   234.1 3950.85   241.6 3952.49     248 3953.47
     257 3952.96   266.4 3954.08   289.5 3958.87     308 3957.96   312.6 3958.24
   326.2 3963.07   339.9 3965.93   394.5 3969.05   408.1  3972.2   422.7 3974.33
#Mann= 3 ,-1,0
       0      .1       0   215.7    .045       0   241.6      .1       0
#XS Ineff= 2 , 0
                          256.88         3963.65
Permanent Ineff=
       F       F
Bank Sta=215.7,241.6
XS Rating Curve= 0 ,0
Exp/Cntr(USF)=0,0
Exp/Cntr=0.3,0.1

Type RM Length L Ch R = 1 ,9242    ,211.1,204.7,193.7
XS GIS Cut Line= 4
2282855.96382195553158.109548775  2282967.651066553245.428666851
2283069.18492422553342.9011707492283195.08690843553436.312320318
#Sta/Elev= 30
       0 4017.53    10.4 4011.97    20.6 4010.59    24.5 4009.36    35.8 4004.35
      46 4001.13    61.2 3995.26    66.3 3993.86    76.4 3989.06    95.9 3983.49
   108.9 3978.26   124.9 3973.43   142.5 3965.07   161.8 3954.72   170.3 3951.78
   173.1 3950.37   175.9 3949.01   181.3 3948.39   204.9 3949.23   214.6 3948.84
   220.23950.352   229.7 3952.97   246.6 3960.67   253.4 3962.99   268.5 3966.28
   296.2 3965.48   400.8  3966.5   410.8 3966.94   423.5 3969.05   439.3 3969.33
#Mann= 5 ,-1,0
       0      .1       0      90     .12       0   173.1    .045       0
   220.2     .12       0  352.52      .1       0
Bank Sta=173.1,220.2
XS Rating Curve= 0 ,0
Exp/Cntr(USF)=0,0
Exp/Cntr=0.3,0.1

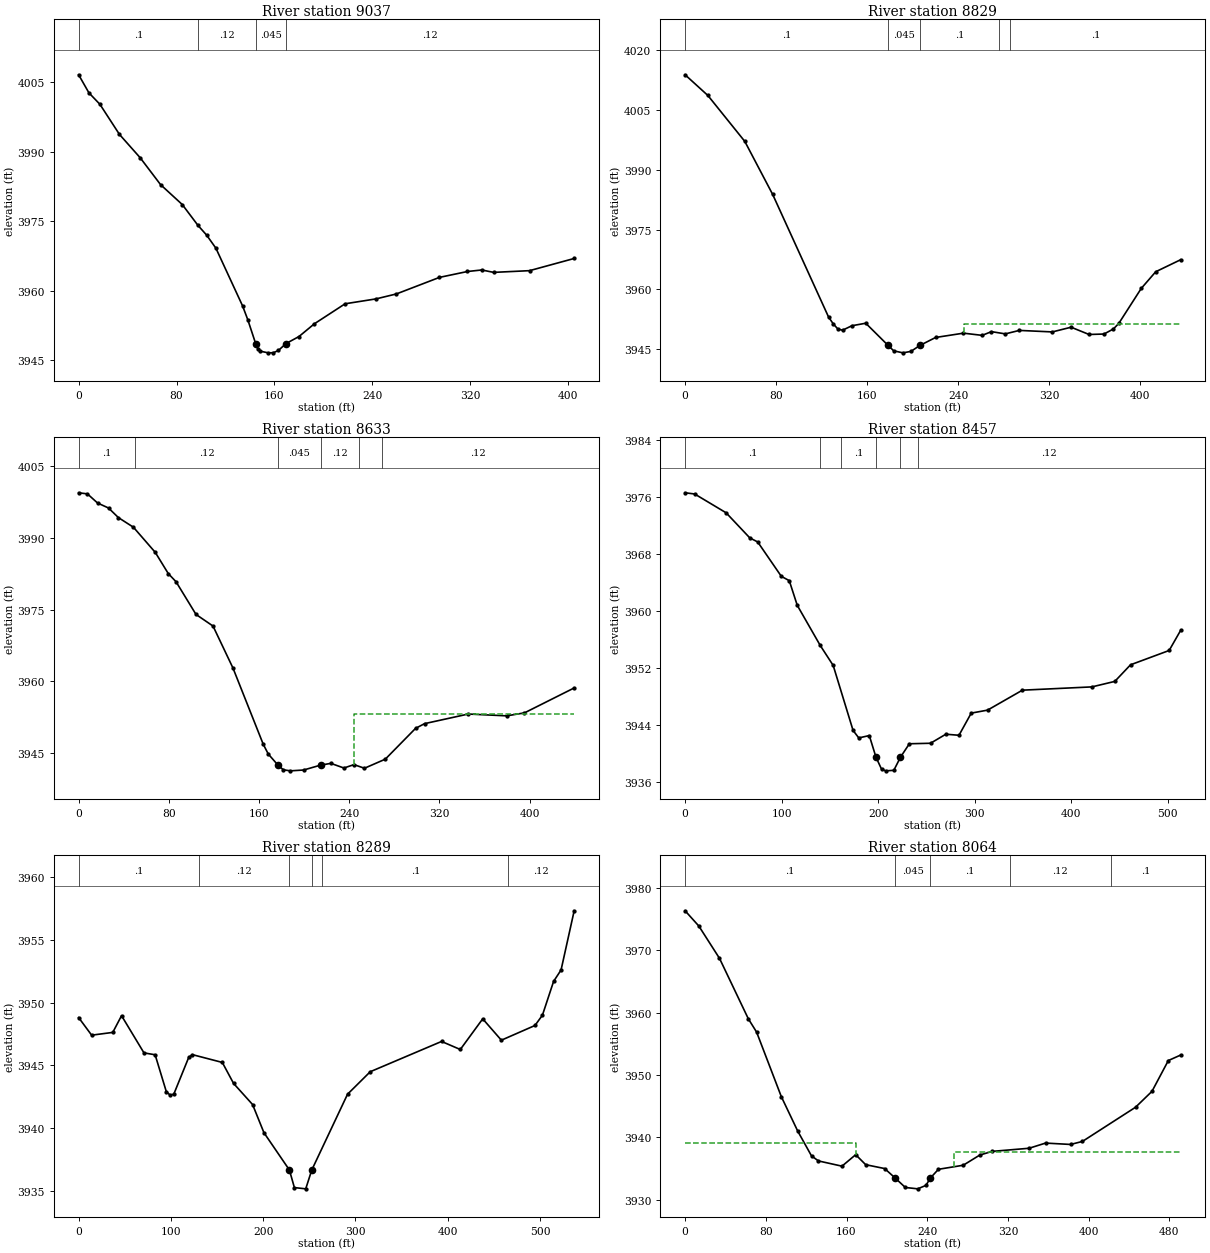
Type RM Length L Ch R = 1 ,9037    ,209.4,208.3,206.2
XS GIS Cut Line= 4
2282732.09251491553387.5760683692282825.50366448553416.005548673
  2282967.651066553460.6804462932283113.85982184553521.600761229
#Sta/Elev= 30
       0 4006.55     8.4 4002.66    17.4 4000.18    33.4 3993.68    50.3 3988.66
      67 3982.85    84.7 3978.57    97.6 3974.05   104.6 3971.98   112.2 3969.15
     134 3956.71   138.2 3953.77   144.73948.572   146.6 3947.34   148.6 3946.94
   154.9 3946.59   159.1 3946.61   163.3  3947.1   169.33948.558   180.1 3950.11
   192.7 3952.86   217.8 3957.17     243 3958.22   259.7 3959.29   294.9 3962.86
   317.8 3964.13   329.5 3964.46   339.2 3963.94   368.5 3964.31     405 3966.94
#Mann= 4 ,-1,0
       0      .1       0   97.64     .12       0   144.7    .045       0
   169.3     .12       0
Bank Sta=144.7,169.3
XS Rating Curve= 0 ,0
Exp/Cntr(USF)=0,0
Exp/Cntr=0.3,0.1

Type RM Length L Ch R = 1 ,8829    ,191.5,196.1,201.6
XS GIS Cut Line= 4
2282652.89610549553596.7358163172282756.46064088553619.073265127
2282937.19090853553657.6561312532283077.30763288553694.208320215
#Sta/Elev= 30
       0 4013.77      20 4008.59    52.5 3997.07      77 3983.78   126.1 3953.08
   130.2 3951.37   134.3 3950.07   138.4 3949.77   146.6 3950.89   158.8 3951.52
   178.43945.973   183.4  3944.6   191.5  3944.1   198.5 3944.46   206.43945.953
   220.2 3947.95   244.7 3949.03   261.1 3948.48   269.3 3949.41   281.5 3948.85
   293.8 3949.72   322.8 3949.34   339.3 3950.52   355.1  3948.7   368.2 3948.81
   376.5 3950.08   381.3  3951.5     401 3960.25   413.7 3964.42   435.6 3967.43
#Mann= 5 ,-1,0
       0      .1       0   178.4    .045       0   206.4      .1       0
  275.95     .12       0  285.95      .1       0
#XS Ineff= 2 , 0
                          244.79         3951.36
Permanent Ineff=
       F       F
Bank Sta=178.4,206.4
XS Rating Curve= 0 ,0
Exp/Cntr(USF)=0,0
Exp/Cntr=0.3,0.1

Type RM Length L Ch R = 1 ,8633    ,176.8,176,171.4
XS GIS Cut Line= 4
2282604.15985354553734.8218635062282730.06183775553793.711501278
2282896.57736524553876.9692650242283006.23393212553909.460099657
#Sta/Elev= 30
       0 3999.39     7.8 3999.16    16.8 3997.25    26.5 3996.21    35.3  3994.2
    48.6 3992.19      68 3986.93    79.5 3982.51    86.4  3980.8   104.1 3973.97
   119.2 3971.54   136.9 3962.76   163.7 3946.86   168.2  3944.8     1773942.434
   181.6  3941.5   187.9 3941.29   199.5 3941.46   214.7 3942.49   223.7 3942.85
   235.3 3941.88   244.2 3942.59   253.5 3941.83     272 3943.73   298.8 3950.16
   306.8 3951.15   345.6 3953.16   379.7 3952.78   395.4  3953.4   439.5 3958.61
#Mann= 6 ,-1,0
       0      .1       0      50     .12       0     177    .045       0
   214.7     .12       0  248.99      .1       0  268.99     .12       0
#XS Ineff= 2 , 0
                          244.24         3953.26
Permanent Ineff=
       F       F
Bank Sta=177,214.7
XS Rating Curve= 0 ,0
Exp/Cntr(USF)=0,0
Exp/Cntr=0.3,0.1

Type RM Length L Ch R = 1 ,8457    ,178.7,168.2,159.2
XS GIS Cut Line= 4
2282494.50328666553917.5828083152282642.74271967553948.042965783
2282799.10486134554000.840572062 2282996.0805463554000.840572062
#Sta/Elev= 30
       0 3976.62     9.9 3976.45    42.5 3973.81      67 3970.29    75.2 3969.72
    99.7 3964.89   107.9 3964.29   116.2 3960.82     140 3955.19   153.4 3952.39
     174 3943.27   179.9 3942.22   190.8 3942.55   197.73939.524   203.5 3937.83
   207.7  3937.6   216.2 3937.67   223.13939.515   232.3  3941.4   254.2 3941.47
   270.1 3942.74   283.7 3942.59   296.4  3945.7   313.3 3946.12   349.4 3948.92
   421.4 3949.38   445.1 3950.15   461.4 3952.48   501.4 3954.49   513.3 3957.31
#Mann= 6 ,-1,0
       0      .1       0     140     .12       0  161.34      .1       0
   197.7    .045       0   223.1      .1       0  241.34     .12       0
Bank Sta=197.7,223.1
XS Rating Curve= 0 ,0
Exp/Cntr(USF)=0,0
Exp/Cntr=0.3,0.1

Type RM Length L Ch R = 1 ,8289    ,223.2,224.5,222.5
XS GIS Cut Line= 4
2282474.19651501 554165.325422392282636.65068818554140.957296415
2282803.16621567554100.343753124 2283002.1725778554069.883595656
#Sta/Elev= 30
       0 3948.81    14.1 3947.41      37 3947.63    46.5 3948.96    70.8    3946
    82.9 3945.85      95 3942.92    99.1 3942.64   103.1 3942.71   119.3 3945.64
   123.3 3945.86   155.7 3945.24   167.9 3943.57   188.5 3941.89   200.8 3939.65
   228.4 3936.68   233.8 3935.28   246.1 3935.18   252.6 3936.67   291.4 3942.71
     316  3944.5   393.3 3946.91   413.6 3946.27   437.9 3948.71   458.1 3947.01
   494.5 3948.18   502.6    3949   514.7 3951.69   522.8  3952.6     537 3957.31
#Mann= 6 ,-1,0
       0      .1       0     130     .12       0   228.4    .045       0
   252.6     .12       0  264.27      .1       0  465.67     .12       0
Bank Sta=228.4,252.6
XS Rating Curve= 0 ,0
Exp/Cntr(USF)=0,0
Exp/Cntr=0.3,0.1

Type RM Length L Ch R = 1 ,8064    ,250.9,250.9,245.1
XS GIS Cut Line= 4
2282518.87141263554384.6385561612282661.01881415554354.178398692
2282823.47298732554317.6262097312283000.14190063554287.166052262
#Sta/Elev= 30
       0  3976.3    13.6 3973.86    34.1 3968.68    62.7 3958.99    70.9 3956.86
    95.4 3946.52   111.7 3940.99   125.3 3937.04   132.2 3936.23   155.5 3935.39
   169.1 3937.23     179 3935.63   197.8 3935.01   208.33933.481   218.3 3931.98
   230.6 3931.76   238.8 3932.32   243.13933.487   251.1 3934.89   275.7 3935.54
   292.1 3937.17   304.4 3937.76     341 3938.26   357.3 3939.09   382.1 3938.87
   393.8 3939.35   446.5 3944.83   462.8 3947.38     479 3952.31   491.2 3953.19
#Mann= 5 ,-1,0
       0      .1       0   208.3    .045       0   243.1      .1       0
  321.89     .12       0  421.89      .1       0
#XS Ineff= 2 , 0
           169.3  3939.1  266.71         3937.62
Permanent Ineff=
       F       F
Bank Sta=208.3,243.1
XS Rating Curve= 0 ,0
Exp/Cntr(USF)=0,0
Exp/Cntr=0.3,0.1

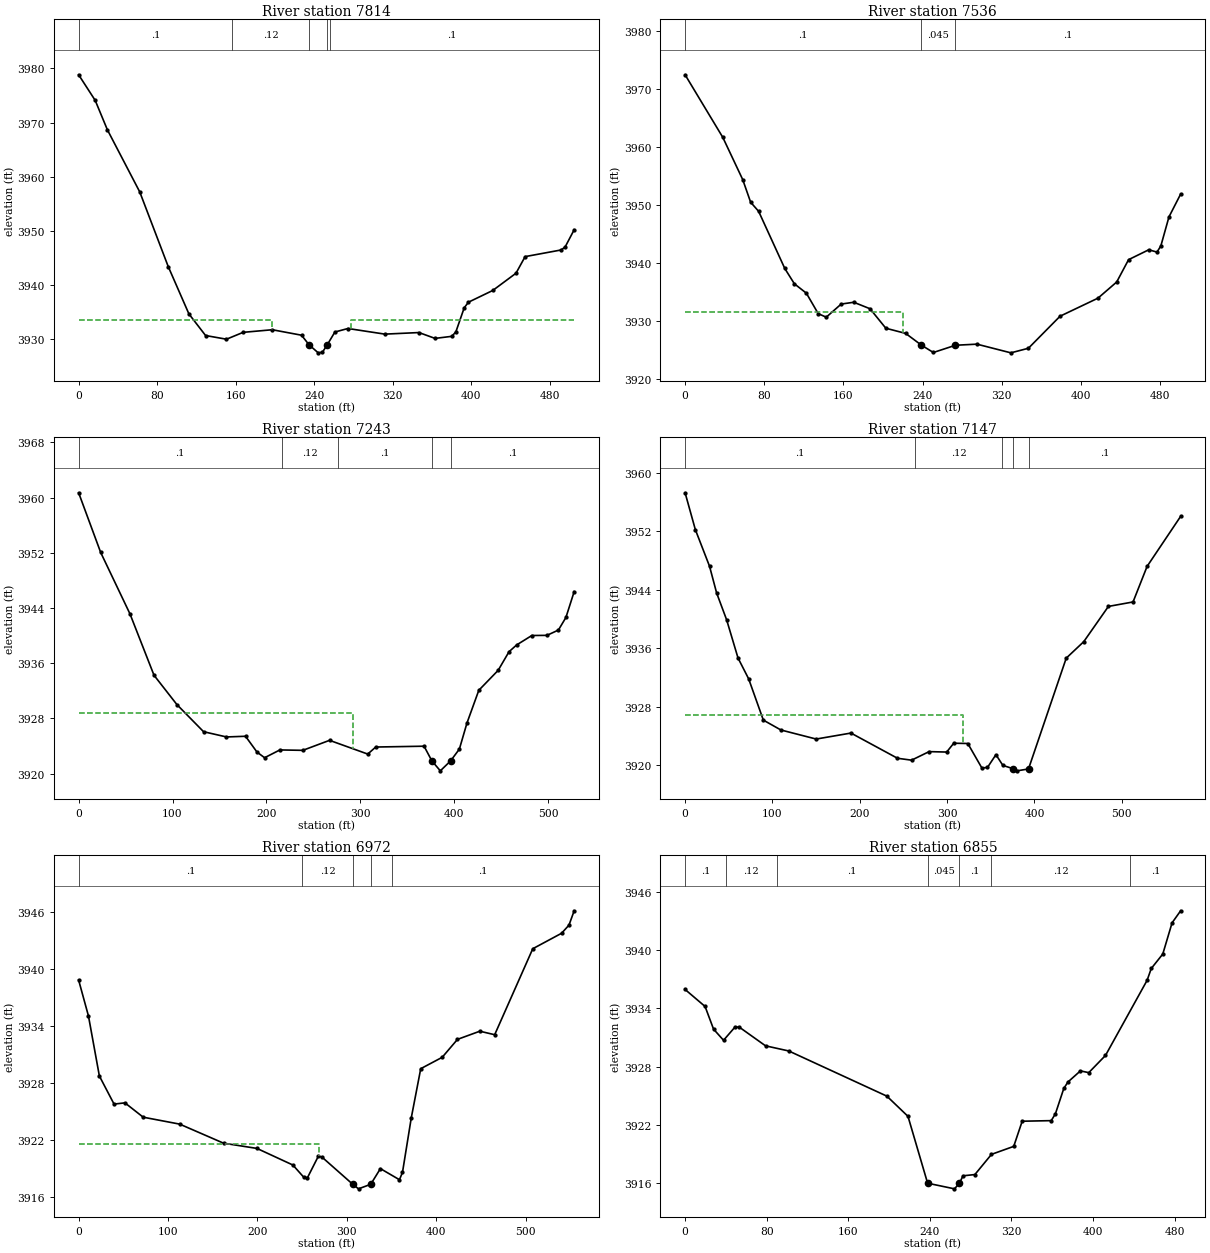
Type RM Length L Ch R = 1 ,7814    ,268,277.6,304.8
XS GIS Cut Line= 4
 2282583.8530819554638.4732017292282677.26423147554614.105075754
2282975.77377466554506.479186033 2283065.1235699554488.203091552
#Sta/Elev= 30
       0 3978.83    16.9 3974.09    29.3 3968.66    62.3 3957.17    91.3 3943.38
   112.4 3934.62   129.4 3930.62   150.7 3929.94   167.7 3931.21   197.4 3931.69
   227.2 3930.68   234.8 3928.92   244.2 3927.42   248.5 3927.53   253.43928.902
   261.2 3931.27   274.5 3931.92   312.1 3930.88   346.9 3931.17   363.3 3930.09
   380.3 3930.47   384.5 3931.29     393 3935.74   397.3 3936.78   422.1 3938.95
   445.8 3942.14   455.1 3945.21   491.8 3946.44   495.9    3947   505.1 3950.18
#Mann= 5 ,-1,0
       0      .1       0  156.54     .12       0   234.8    .045       0
   253.4     .12       0  256.54      .1       0
#XS Ineff= 2 , 0
          197.56  3933.4  277.35         3933.49
Permanent Ineff=
       F       F
Bank Sta=234.8,253.4
XS Rating Curve= 0 ,0
Exp/Cntr(USF)=0,0
Exp/Cntr=0.3,0.1

Type RM Length L Ch R = 1 ,7536    ,298.5,293.3,260.6
XS GIS Cut Line= 4
2282610.25188504 554813.11143788 2282801.1355385554794.835343399
2282998.11122347554794.8353433992283107.76779035554772.497894589
#Sta/Elev= 30
       0  3972.5    38.1 3961.68    58.2 3954.39    66.2 3950.48    74.3  3948.9
   100.7 3939.03   110.4 3936.38   122.5 3934.76   134.5 3931.22   142.6 3930.61
   157.7 3932.88   170.4 3933.19   186.8 3932.07   202.8  3928.7   222.8 3927.81
   238.8 3925.77   250.8 3924.51   273.1 3925.76   294.8 3925.95   329.1 3924.45
   346.8 3925.24   378.8 3930.78   417.1  3933.9     436 3936.69     448 3940.55
   468.4 3942.26   476.7 3941.86   480.6 3942.92   488.8 3947.94   500.6 3951.88
#Mann= 3 ,-1,0
       0      .1       0   238.8    .045       0   273.1      .1       0
#XS Ineff= 2 , 0
          220.42 3931.45
Permanent Ineff=
       F       F
Bank Sta=238.8,273.1
XS Rating Curve= 0 ,0
Exp/Cntr(USF)=0,0
Exp/Cntr=0.3,0.1

Type RM Length L Ch R = 1 ,7243    ,93.8,95.2,96
XS GIS Cut Line= 4
2282656.95745982555068.976760612 2282801.1355385555044.608634638
2283107.76779035554987.7496740312283176.81081395554977.596288208
#Sta/Elev= 30
       0  3960.7    23.5 3952.05    54.7 3943.15    80.3 3934.26   104.7 3930.01
   133.1 3926.08   157.5 3925.32   177.8 3925.42     190 3923.13   198.1 3922.31
   214.4 3923.44   238.8 3923.38   267.3 3924.83     308 3922.84   316.5 3923.86
     368 3923.98   376.33921.855   385.3 3920.41   396.23921.843   405.6 3923.56
   413.7 3927.34   426.3 3932.08   446.9 3934.97   458.5 3937.67   466.6 3938.65
   482.8 3940.02   498.9 3940.04   511.1 3940.81   519.1 3942.63   527.9 3946.38
#Mann= 5 ,-1,0
       0      .1       0  216.22     .12       0  276.22      .1       0
   376.3    .045       0   396.2      .1       0
#XS Ineff= 2 , 0
          292.08 3928.73
Permanent Ineff=
       F       F
Bank Sta=376.3,396.2
XS Rating Curve= 0 ,0
Exp/Cntr(USF)=0,0
Exp/Cntr=0.3,0.1

Type RM Length L Ch R = 1 ,7147    ,173.2,175,180.6
XS GIS Cut Line= 3
2282664.66135842555081.1417475622282854.47292952555116.870984474
2283226.28030113555074.442515641
#Sta/Elev= 30
       0 3957.28    11.7 3952.25      28 3947.22    36.1 3943.57    47.6 3939.88
    60.6 3934.67    72.8 3931.81    89.6 3926.17   109.7 3924.82   150.1 3923.58
   189.9  3924.4   243.2 3920.95   259.3 3920.69   279.4 3921.86   299.5  3921.8
   307.6 3923.01   323.7 3922.97   339.8 3919.62   346.2 3919.69   355.9 3921.44
   363.9 3919.97     376 3919.51   380.1 3919.23   393.2 3919.49   436.4 3934.65
   456.5 3936.91   484.7 3941.73   512.9 3942.34     529 3947.21   567.4 3954.05
#Mann= 5 ,-1,0
       0      .1       0  263.15     .12       0  363.15      .1       0
     376    .045       0   393.2      .1       0
#XS Ineff= 2 , 0
          318.76 3926.92
Permanent Ineff=
       F       F
Bank Sta=376,393.2
XS Rating Curve= 0 ,0
Exp/Cntr(USF)=0,0
Exp/Cntr=0.3,0.1

Type RM Length L Ch R = 1 ,6972    ,125.1,117.4,107.6
XS GIS Cut Line= 3
2282681.40943822555192.7956129122283071.08142829 555272.06985731
2283221.81414652555229.641388478
#Sta/Elev= 30
       0 3938.81      11 3935.02    23.2  3928.7    39.6 3925.74    51.8 3925.87
    72.2 3924.36     113 3923.63   162.1 3921.62   199.4 3921.07   239.6 3919.32
   251.8 3918.03   255.9 3917.98   268.1 3920.25   272.2 3920.15   306.7 3917.28
     313 3916.81  326.69 3917.29   337.5 3918.94   358.8 3917.77   362.2 3918.55
     372 3924.28   382.6 3929.47   406.6 3930.67   423.7 3932.56   448.7 3933.42
   465.3 3933.05   507.9 3942.11   540.1 3943.74   548.4  3944.6   554.2 3946.11
#Mann= 5 ,-1,0
       0      .1       0     250     .12       0   306.7    .045       0
  326.69     .12       0     350      .1       0
#XS Ineff= 2 , 0
          268.73  3921.5
Permanent Ineff=
       F       F
Bank Sta=306.7,326.69
XS Rating Curve= 0 ,0
Exp/Cntr(USF)=0,0
Exp/Cntr=0.3,0.1

Type RM Length L Ch R = 1 ,6855    ,95.5,95.6,96.7
XS GIS Cut Line= 4
 2282737.2363709555435.0845007212283028.65295946555355.810256323
2283052.10027118555349.1110244022283208.41568267 555316.73140345
#Sta/Elev= 30
       0 3935.93    19.6 3934.18    27.9 3931.85    37.7  3930.7    48.6 3932.02
    52.8 3932.08    78.9 3930.13   101.7  3929.6   197.9 3924.95   218.6 3922.87
  237.85 3915.99   264.2 3915.41   269.1 3915.99   272.5 3916.75   284.2 3916.88
   300.5 3918.96   322.3 3919.78   330.6 3922.37   359.1 3922.43   363.2 3923.14
   371.4 3925.74   375.5 3926.41   387.7 3927.55   395.9 3927.37   412.3 3929.14
   453.1 3936.87   457.2 3938.09   468.5 3939.58   477.6 3942.79     486 3944.03
#Mann= 7 ,-1,0
       0      .1       0      40     .12       0      90      .1       0
  237.85    .045       0   269.1      .1       0     300     .12       0
  436.39      .1       0
Bank Sta=237.85,269.1
XS Rating Curve= 0 ,0
Exp/Cntr(USF)=0,0
Exp/Cntr=0.3,0.1

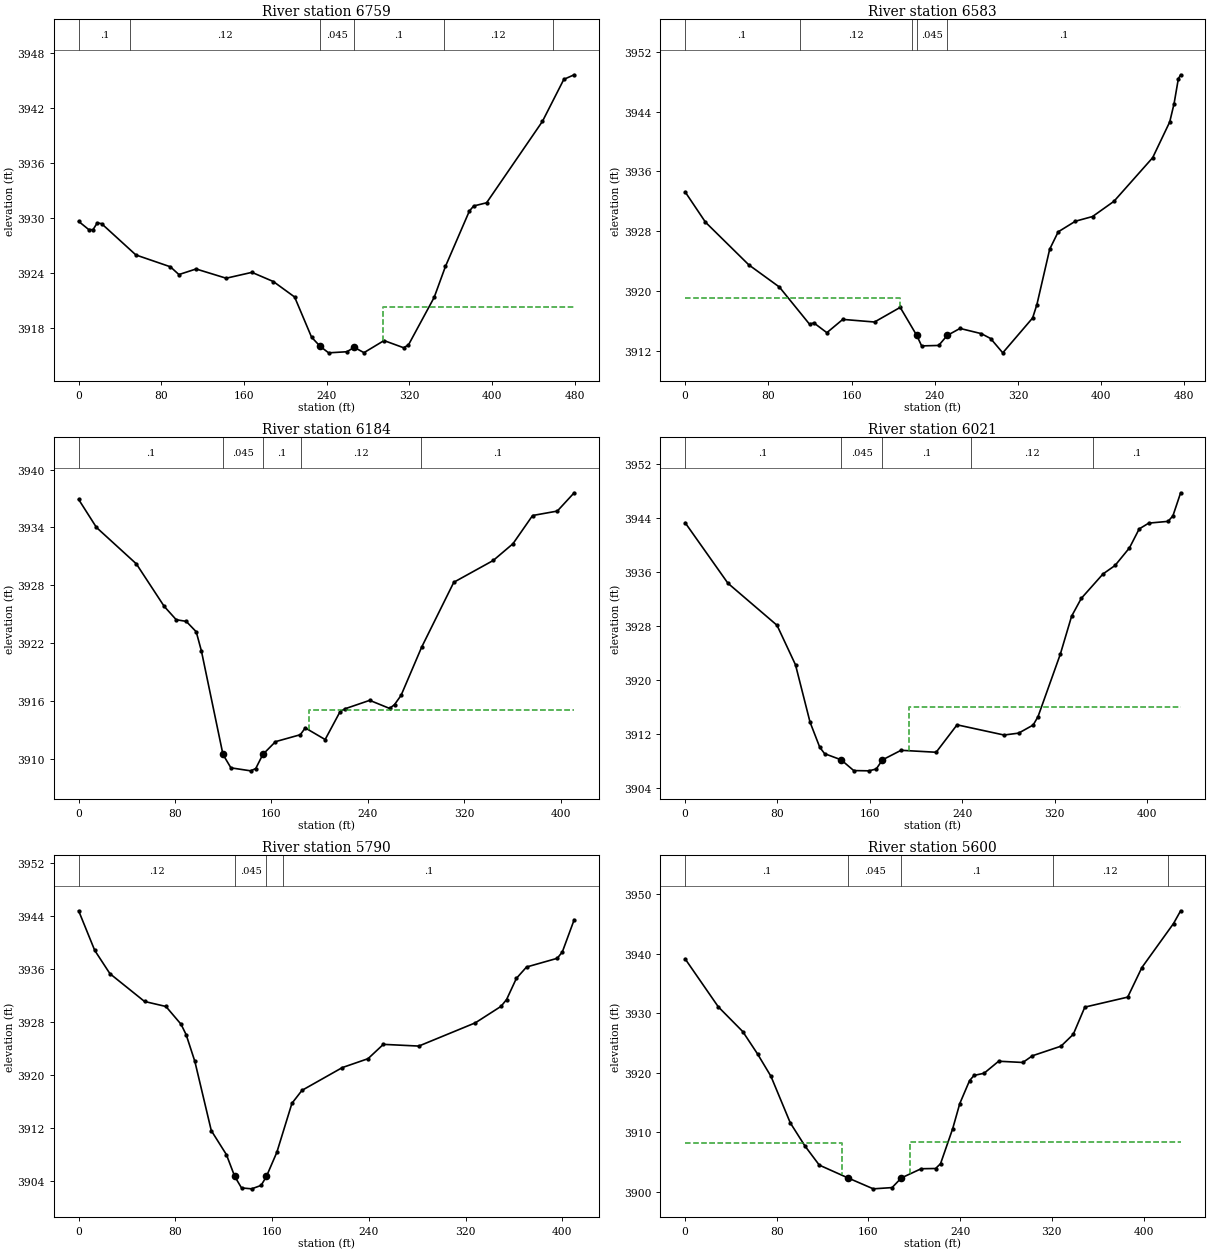
Type RM Length L Ch R = 1 ,6759    ,175.7,175.9,176.6
XS GIS Cut Line= 4
2282778.79808969555521.8177683062282945.31361719555475.112193521
2283126.04388483555430.4372959012283241.79248321555397.946461269
#Sta/Elev= 30
       0 3929.64     9.7 3928.75    13.9 3928.73      18 3929.47    22.2 3929.39
    55.4 3925.97    88.7 3924.68      97 3923.83   113.6 3924.44   142.7 3923.43
   167.6 3924.07   188.3 3923.07   208.9 3921.38   225.3 3916.99   233.6 3915.99
   241.8 3915.28   259.5  3915.4   266.5 3915.88     276  3915.3   295.4 3916.62
   314.3 3915.84     319 3916.14   343.9 3921.34   354.8 3924.72   377.9 3930.76
   382.1 3931.32   394.6 3931.67   448.6 3940.56   469.3 3945.15   479.3 3945.65
#Mann= 6 ,-1,0
       0      .1       0      50     .12       0   233.6    .045       0
   266.5      .1       0  352.94     .12       0  459.11      .1       0
#XS Ineff= 2 , 0
                          294.28         3920.25
Permanent Ineff=
       F       F
Bank Sta=233.6,266.5
XS Rating Curve= 0 ,0
Exp/Cntr(USF)=0,0
Exp/Cntr=0.3,0.1

Type RM Length L Ch R = 1 ,6583    ,394.9,399.4,396.2
XS GIS Cut Line= 4
2282817.38095582555694.4253272922282998.11122347555641.627721014
2283164.62675096555603.0448548882283278.34467217555574.615374584
#Sta/Elev= 30
       0 3933.27    19.6  3929.2    61.3 3923.48    90.6 3920.52   119.6 3915.54
   123.8 3915.71   136.3  3914.4   151.6 3916.18   182.1 3915.83   206.8 3917.79
   222.73914.035   227.4 3912.63   243.8 3912.69     252 3914.03   264.3 3914.97
   284.8 3914.27   293.7 3913.62   305.4  3911.7   334.1 3916.37   338.2 3918.16
   350.5 3925.58   358.7 3927.91   375.2 3929.33   391.7 3929.96   412.3    3932
   449.5 3937.84   465.9 3942.63   470.1 3945.09   474.2 3948.42   476.4 3948.95
#Mann= 5 ,-1,0
       0      .1       0     110     .12       0  218.28      .1       0
   222.7    .045       0     252      .1       0
#XS Ineff= 2 , 0
          206.33 3919.11
Permanent Ineff=
       F       F
Bank Sta=222.7,252
XS Rating Curve= 0 ,0
Exp/Cntr(USF)=0,0
Exp/Cntr=0.3,0.1

Type RM Length L Ch R = 1 ,6184    ,165,163.5,161.7
XS GIS Cut Line= 4
2282849.87179045555895.4623665822282941.25226286555871.094240608
2283126.04388483555826.4193429882283249.91519187555800.020539849
#Sta/Elev= 30
       0  3936.9    14.8 3933.99    47.9 3930.21      71  3925.8      81 3924.41
    89.3 3924.24    97.6 3923.16   101.9 3921.17   119.83910.419   126.4 3909.03
   142.8 3908.72     147 3908.96   152.93910.423   163.4 3911.75     184 3912.47
   188.1 3913.18   204.6 3911.97   216.9 3914.84     221 3915.16   241.6 3916.04
   258.1  3915.2   262.2  3915.6   267.6 3916.55   284.7 3921.56   311.4  3928.3
   344.1 3930.56   360.5  3932.3   376.8 3935.23   397.3 3935.69   411.3 3937.59
#Mann= 5 ,-1,0
       0      .1       0   119.8    .045       0   152.9      .1       0
  184.57     .12       0  284.57      .1       0
#XS Ineff= 2 , 0
                          191.59         3914.99
Permanent Ineff=
       F       F
Bank Sta=119.8,152.9
XS Rating Curve= 0 ,0
Exp/Cntr(USF)=0,0
Exp/Cntr=0.3,0.1

Type RM Length L Ch R = 1 ,6021    ,230.2,231,231.6
XS GIS Cut Line= 4
2282888.45465658 556059.947216912282953.43632585556041.671122429
2283168.68810529555972.6280988352283298.65144382555934.045232709
#Sta/Elev= 30
       0 3943.28    37.1 3934.31    79.6 3928.09    95.6 3922.24   108.2 3913.75
   116.6 3910.04   120.8 3909.09   135.13908.183     146 3906.59   159.1 3906.55
   165.5 3906.82   170.93908.174     187 3909.59   217.4  3909.3   235.5 3913.36
   276.2 3911.85   288.8 3912.13   301.4 3913.33   305.6 3914.57   324.9 3923.81
   334.7 3929.44   343.1 3932.08   361.9 3935.69   372.3 3936.94   384.8 3939.55
   393.2 3942.35   401.5 3943.21   418.2 3943.47   422.4 3944.28   429.1  3947.7
#Mann= 5 ,-1,0
       0      .1       0   135.1    .045       0   170.9      .1       0
   247.5     .12       0  353.56      .1       0
#XS Ineff= 2 , 0
                          193.55         3916.02
Permanent Ineff=
       F       F
Bank Sta=135.1,170.9
XS Rating Curve= 0 ,0
Exp/Cntr(USF)=0,0
Exp/Cntr=0.3,0.1

Type RM Length L Ch R = 1 ,5790    ,187.9,189.3,188.2
XS GIS Cut Line= 4
2282959.52835734556277.2296735172283034.66341243556252.861547542
2283166.65742812556214.2786814162283349.41837293556151.327689315
#Sta/Elev= 30
       0 3944.81    13.3 3938.82    25.9 3935.29    54.5 3931.09    72.2 3930.33
    84.7 3927.64    88.9 3926.07    96.1 3922.03   109.7 3911.55   122.2 3907.92
   129.1 3904.61   134.7 3902.88   143.1 3902.74   150.9 3903.26   155.33904.615
   163.9 3908.26   176.4 3915.68   184.7 3917.64   218.1 3921.09   239.3 3922.43
     252  3924.6   281.3 3924.34   328.1 3927.86   349.3 3930.35   353.9 3931.38
     362 3934.58   370.4  3936.3   395.8 3937.62     400 3938.58   409.8 3943.45
#Mann= 4 ,-1,0
       0     .12       0   129.1    .045       0   155.3     .12       0
  168.99      .1       0
Bank Sta=129.1,155.3
XS Rating Curve= 0 ,0
Exp/Cntr(USF)=0,0
Exp/Cntr=0.3,0.1

Type RM Length L Ch R = 1 ,5600    ,207,200.9,201.1
XS GIS Cut Line= 4
2283016.38731795556455.9292639972283091.52237304556433.591815187
2283292.55941233556364.5487915922283428.61478235556325.965925466
#Sta/Elev= 30
       0 3939.18      29  3931.1    50.3 3926.95    63.2 3923.19    74.9 3919.43
    91.8 3911.59   104.5 3907.73   117.1 3904.49   142.13902.339   164.2  3900.5
   180.6 3900.71   188.73902.336     206 3903.88   218.6 3903.92   222.9 3904.73
   233.5 3910.62   239.7 3914.85   248.2 3918.69   252.1 3919.57   260.9 3919.94
   273.6 3921.96   294.7 3921.75   303.1 3922.88     328 3924.49   338.7 3926.48
   348.8 3931.06   386.2 3932.74   398.6 3937.72   426.2 3945.12   432.4 3947.26
#Mann= 5 ,-1,0
       0      .1       0   142.1    .045       0   188.7      .1       0
  320.95     .12       0  420.95      .1       0
#XS Ineff= 2 , 0
          136.96 3908.25  196.37         3908.33
Permanent Ineff=
       F       F
Bank Sta=142.1,188.7
XS Rating Curve= 0 ,0
Exp/Cntr(USF)=0,0
Exp/Cntr=0.3,0.1