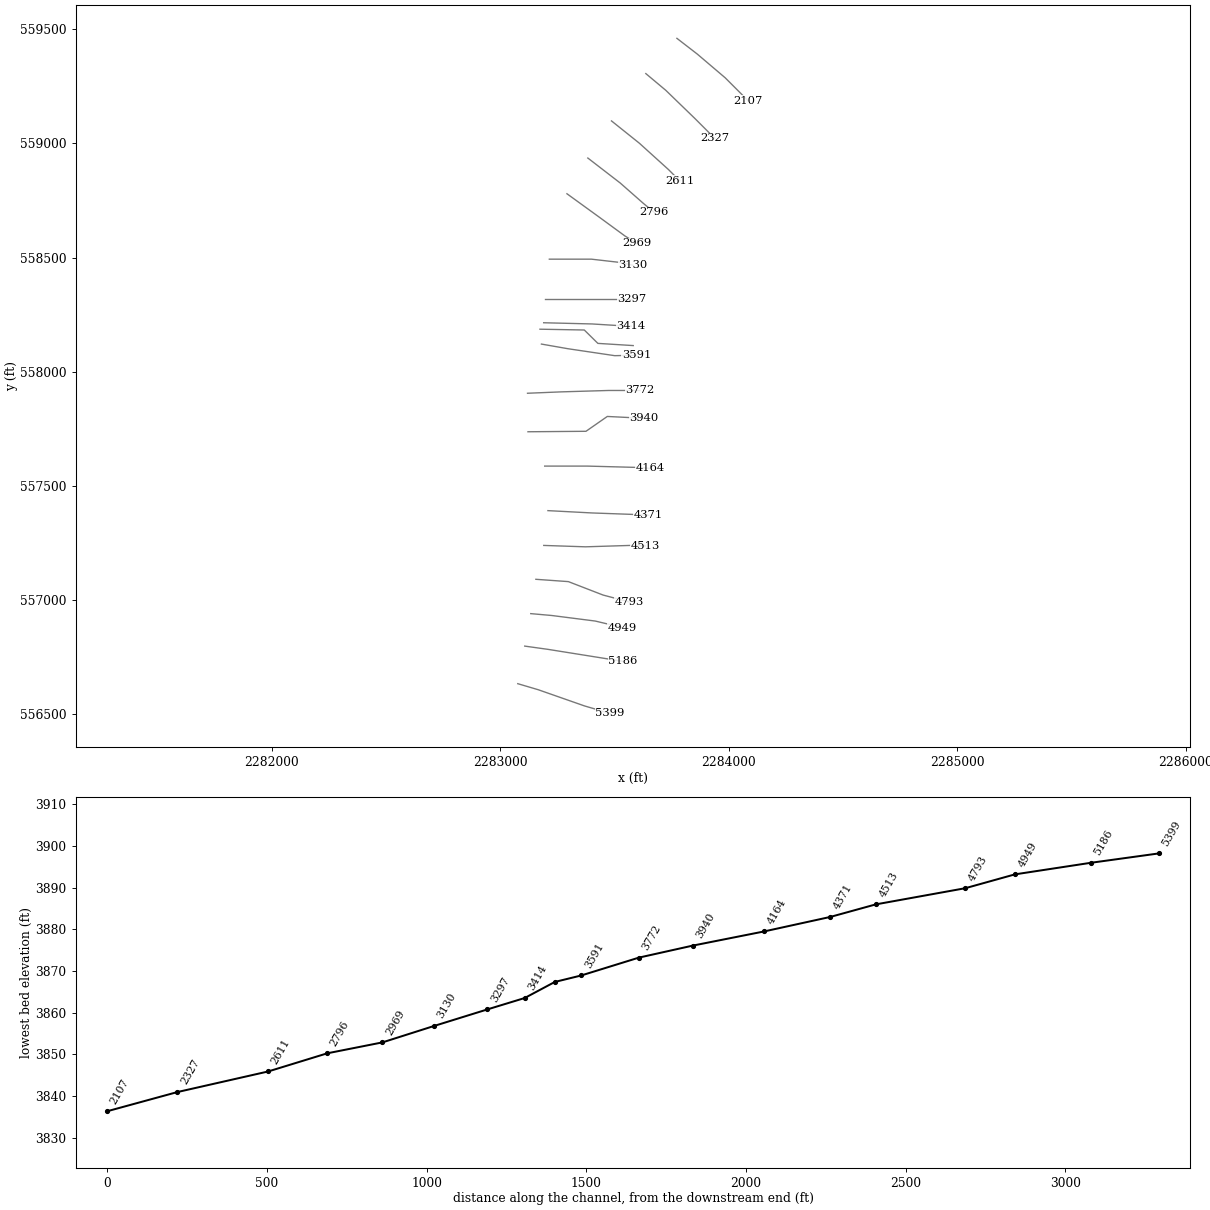
HEC-RAS study FIRSTFK.prj: FIRSTFK

--- FIRSTFK.g01 (geometry) --- (continued)

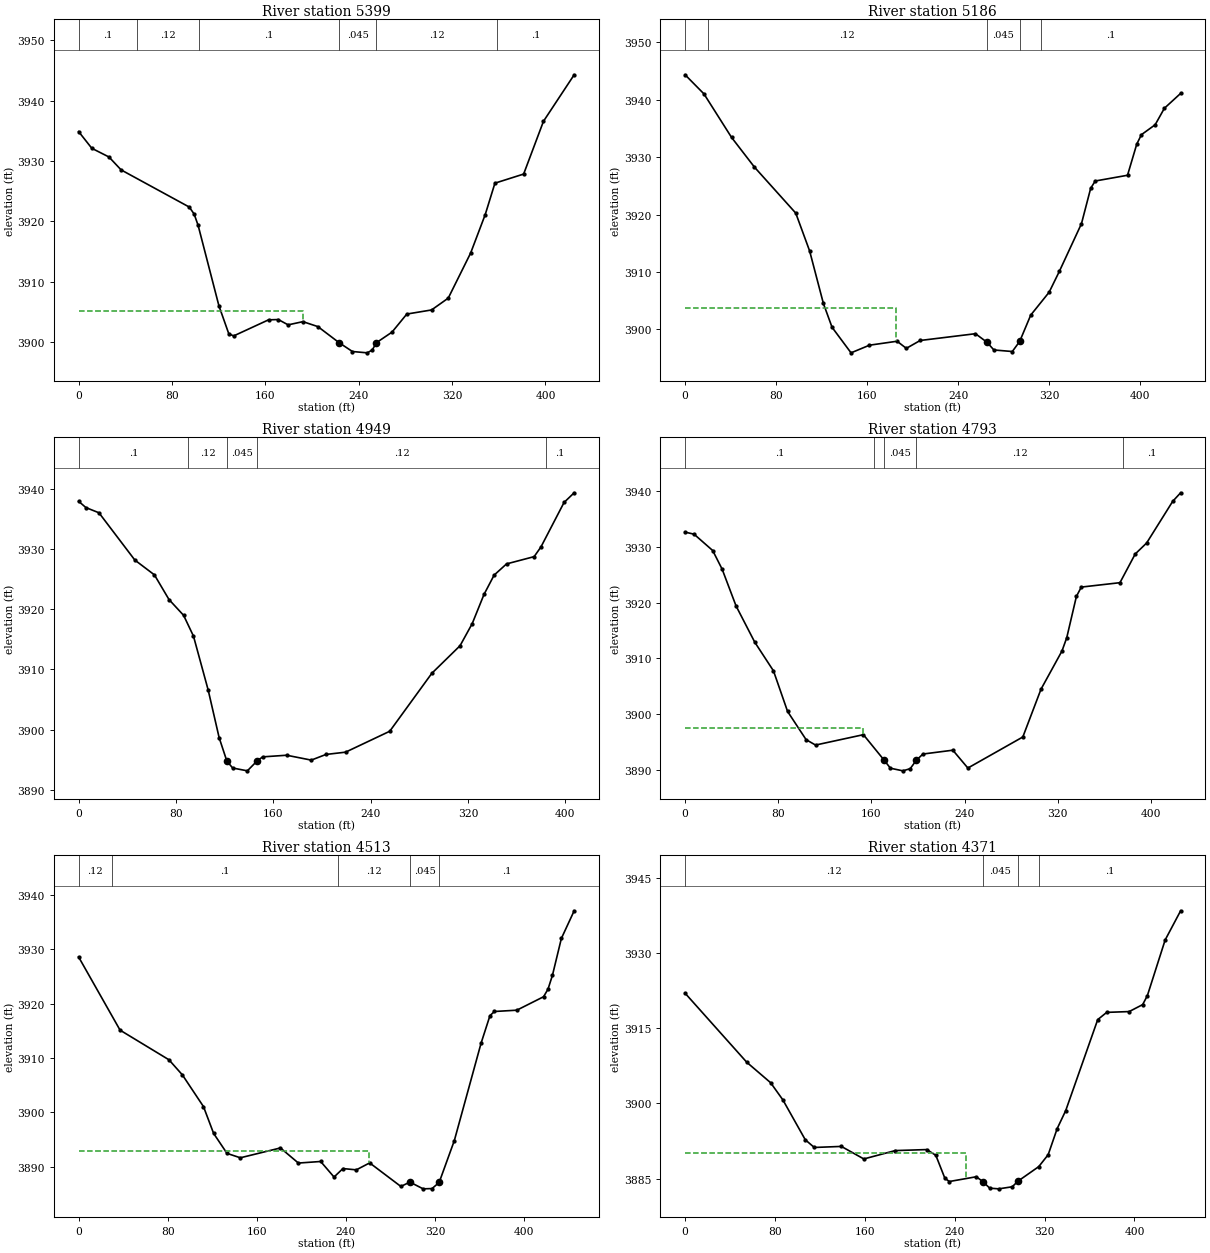
Type RM Length L Ch R = 1 ,5399    ,211.2,213.9,217.8
XS GIS Cut Line= 4
2283077.30763288556634.6288544772283166.65742812556608.230051338
2283369.72514458556537.1563505792283481.41238863556504.665515946
#Sta/Elev= 30
       0 3934.87    11.3  3932.1      26 3930.66    36.4 3928.52    94.8 3922.36
      99 3921.19   102.4 3919.31   120.2 3905.99   128.7 3901.33   132.9    3901
   162.7 3903.66   171.1 3903.71   179.5 3902.83   192.2 3903.36     205 3902.54
   223.33899.857   234.6 3898.41   247.3 3898.19   251.6 3898.66   255.13899.866
   268.5 3901.62   281.2 3904.62   302.4  3905.3   316.7 3907.26   335.9 3914.74
   348.4 3921.12   356.7 3926.32   381.3 3927.83   398.3 3936.58   424.6 3944.29
#Mann= 6 ,-1,0
       0      .1       0      50     .12       0  103.17      .1       0
   223.3    .045       0   255.1     .12       0  358.31      .1       0
#XS Ineff= 2 , 0
          192.31 3905.09
Permanent Ineff=
       F       F
Bank Sta=223.3,255.1
XS Rating Curve= 0 ,0
Exp/Cntr(USF)=0,0
Exp/Cntr=0.3,0.1

Type RM Length L Ch R = 1 ,5186    ,237.2,236.9,241.5
XS GIS Cut Line= 4
2283107.76779035556799.1137048052283209.30164858556784.898964653
2283450.95223116556746.3160985272283538.27134923556732.101358375
#Sta/Elev= 30
       0 3944.33    16.6    3941    40.8 3933.44      61 3928.25    97.3 3920.25
   109.5 3913.66   121.6 3904.52   129.2 3900.38   145.9 3895.93   162.1 3897.26
   186.4 3897.95   194.5 3896.71   206.7 3898.08   255.3 3899.26   265.4 3897.78
   271.5 3896.43   287.7 3896.16   294.23897.924   303.9  3902.5   320.1 3906.49
   329.1 3910.13   348.5 3918.41   356.6 3924.57   360.6 3925.84     389 3926.84
   397.1 3932.25   401.2  3933.9   413.3 3935.63   421.4  3938.5   435.7 3941.09
#Mann= 5 ,-1,0
       0      .1       0      20     .12       0   265.4    .045       0
   294.2     .12       0  312.52      .1       0
#XS Ineff= 2 , 0
          185.84 3903.76
Permanent Ineff=
       F       F
Bank Sta=265.4,294.2
XS Rating Curve= 0 ,0
Exp/Cntr(USF)=0,0
Exp/Cntr=0.3,0.1

Type RM Length L Ch R = 1 ,4949    ,160.2,155.4,152.2
XS GIS Cut Line= 4
2283134.16659349556941.261106323 2283225.5470659556933.138397665
2283416.43071936556908.7702716912283536.24067207556880.340791387
#Sta/Elev= 30
       0 3937.91       6 3936.86    16.7    3936    46.2 3928.15    62.3 3925.69
    74.3 3921.59    86.3 3918.97    94.4 3915.52   106.5 3906.56   115.5 3898.66
   121.83894.796   126.6 3893.63   138.7 3893.16   146.8 3894.83   151.3 3895.48
     171 3895.75   191.2 3894.94   203.3 3895.88   219.4 3896.26   255.7 3899.73
   290.3 3909.35   313.5 3913.93   323.5  3917.6   333.2 3922.45   341.5 3925.65
   351.7 3927.51   374.4 3928.72     380 3930.33     399 3937.72   407.3 3939.32
#Mann= 5 ,-1,0
       0      .1       0      90     .12       0   121.8    .045       0
   146.8     .12       0  384.17      .1       0
Bank Sta=121.8,146.8
XS Rating Curve= 0 ,0
Exp/Cntr(USF)=0,0
Exp/Cntr=0.3,0.1

Type RM Length L Ch R = 1 ,4793    ,269.2,280.1,282.6
XS GIS Cut Line= 4
 2283156.5040423  557091.53121652283298.65144382557081.377830677
2283450.95223116557022.4881929052283566.70082954556992.028035437
#Sta/Elev= 30
       0 3932.62     7.7 3932.25    23.7 3929.32    31.8 3925.98    43.8 3919.37
    59.8  3912.9    75.9 3907.75      88 3900.48   103.9 3895.43     112 3894.46
   153.1 3896.32   170.93891.753   176.3 3890.31     187 3889.84   193.3 3890.23
   198.5 3891.72   204.2 3892.85   229.9 3893.54   242.8 3890.34     290 3895.91
   305.6 3904.47   323.6 3911.31   327.7 3913.69     336  3921.1   340.2 3922.77
   373.4 3923.56   386.5  3928.7   396.3 3930.67   418.7 3938.14   425.5 3939.67
#Mann= 5 ,-1,0
       0      .1       0  162.51     .12       0   170.9    .045       0
   198.5     .12       0   375.8      .1       0
#XS Ineff= 2 , 0
          153.13 3897.57
Permanent Ineff=
       F       F
Bank Sta=170.9,198.5
XS Rating Curve= 0 ,0
Exp/Cntr(USF)=0,0
Exp/Cntr=0.3,0.1

Type RM Length L Ch R = 1 ,4513    ,143.6,142.4,140.6
XS GIS Cut Line= 4
 2283191.0255541557239.7706495112283373.78649891557233.678618018
 2283568.7315067557239.7706495112283635.74385313557237.739972347
#Sta/Elev= 30
       0 3928.59    37.2 3915.14    81.1 3909.69    93.2  3906.9   112.1 3901.08
   121.2 3896.15   133.2 3892.48   145.2 3891.67   181.2 3893.48   197.3  3890.7
   217.3 3890.99   229.3 3888.13   237.3 3889.69   249.3 3889.45   261.3 3890.73
   289.3  3886.4   297.4  3887.2   309.3 3885.96   317.3 3886.01   323.7 3887.14
   337.3 3894.83   361.3 3912.73   369.3 3917.81   373.3 3918.57   393.4 3918.81
   417.4 3921.28   421.4 3922.67   425.4 3925.23   433.4    3932   444.9 3937.09
#Mann= 5 ,-1,0
       0     .12       0      30      .1       0  232.86     .12       0
   297.4    .045       0   323.7      .1       0
#XS Ineff= 2 , 0
          260.96 3892.96
Permanent Ineff=
       F       F
Bank Sta=297.4,323.7
XS Rating Curve= 0 ,0
Exp/Cntr(USF)=0,0
Exp/Cntr=0.3,0.1

Type RM Length L Ch R = 1 ,4371    ,206.8,206.6,206.8
XS GIS Cut Line= 4
2283209.30164858557392.0714368522283402.21597921 557381.91805103
2283572.79286103557375.8260195362283649.95859329557371.764665207
#Sta/Elev= 30
       0 3921.96    54.9 3908.19    76.1 3904.12      87  3900.7     107 3892.73
     115  3891.2   139.1 3891.41   159.1 3888.91   187.1 3890.58   215.2 3890.78
   223.2 3889.63   231.2 3885.08   235.2 3884.41   259.2 3885.36     265  3884.4
   271.2 3883.08   279.2 3882.95   291.2 3883.36   296.3 3884.48   314.8 3887.38
   323.2 3889.76   331.2 3894.96   338.8 3898.55   367.3  3916.7   375.3 3918.14
   395.3  3918.3   407.3 3919.69   411.5 3921.49   427.3 3932.57   441.1  3938.4
#Mann= 4 ,-1,0
       0     .12       0     265    .045       0   296.3     .12       0
   314.8      .1       0
#XS Ineff= 2 , 0
             250    3890
Permanent Ineff=
       F       F
Bank Sta=265,296.3
XS Rating Curve= 0 ,0
Exp/Cntr(USF)=0,0
Exp/Cntr=0.3,0.1

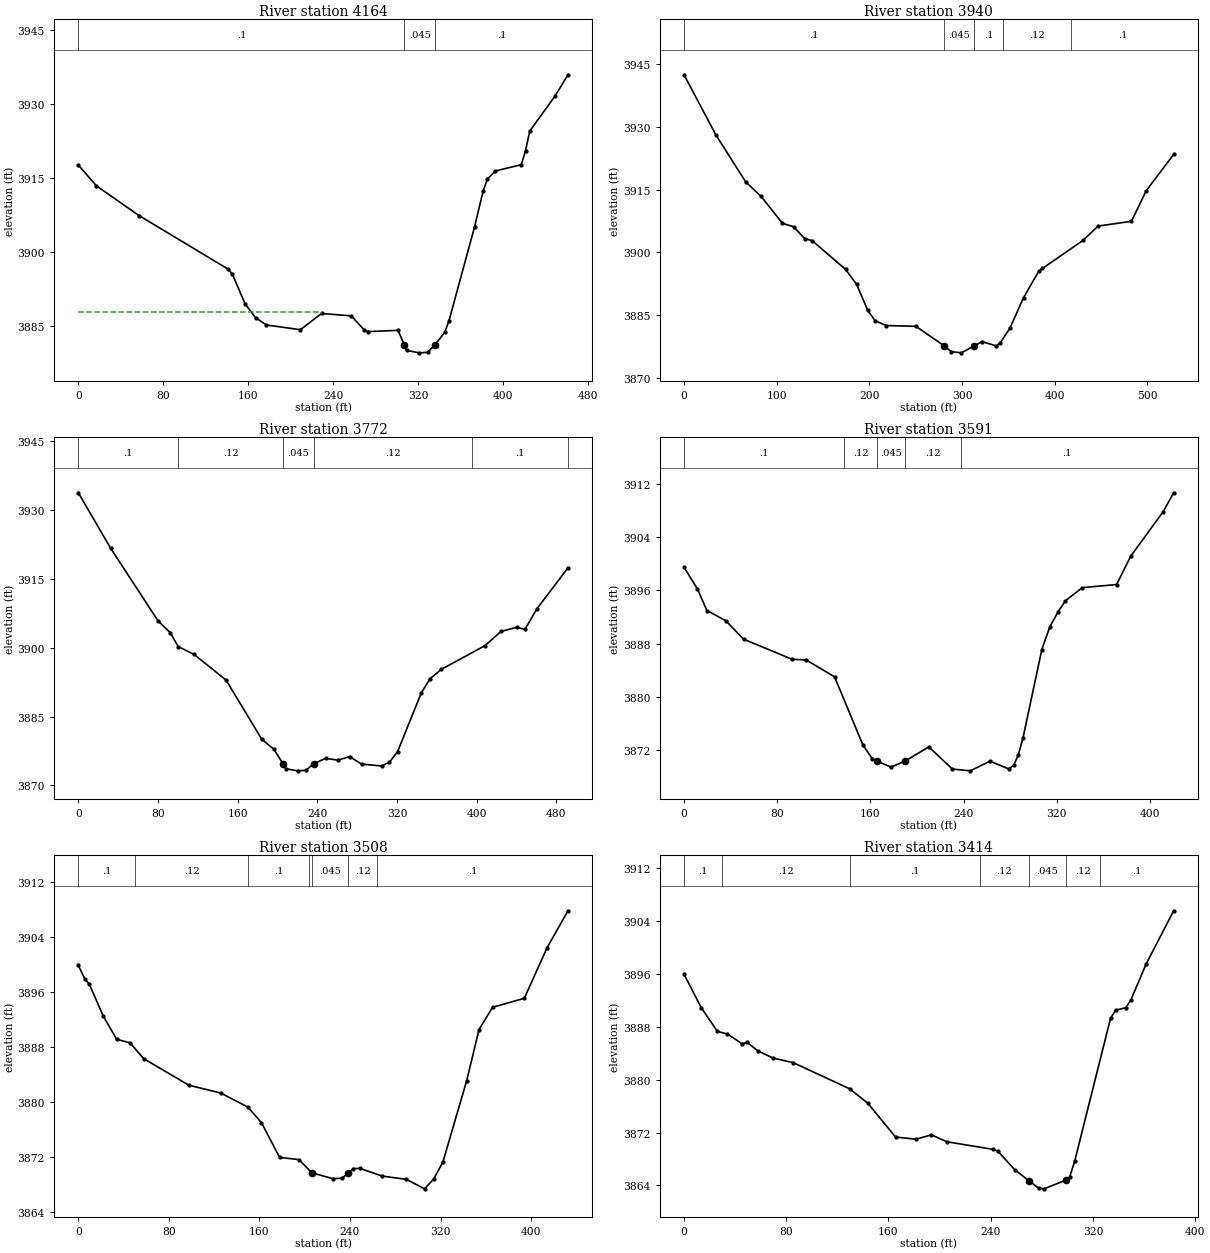
Type RM Length L Ch R = 1 ,4164    ,213.5,224.6,237.3
XS GIS Cut Line= 4
2283195.08690843557587.0164446492283381.90920756557587.016444649
2283609.34504999557580.9244131552283656.05062478557576.863058826
#Sta/Elev= 30
       0 3917.53    17.1 3913.32    57.1 3907.32   141.1 3896.45   145.1 3895.42
   157.1  3889.4   166.9 3886.62   177.1 3885.13   209.1 3884.17   229.1 3887.46
   257.2 3886.97   269.1 3884.14   273.1 3883.79   301.1 3884.04   307.23881.057
   309.1 3879.98   321.1 3879.48   329.1 3879.58   335.73881.056   345.1 3883.63
   349.1 3885.96   373.2 3905.02   381.2 3912.23   385.2 3914.69   392.8 3916.35
   417.2 3917.62   421.2 3920.45   425.2 3924.45   449.3 3931.62   461.2 3935.85
#Mann= 3 ,-1,0
       0      .1       0   307.2    .045       0   335.7      .1       0
#XS Ineff= 2 , 0
          228.25 3887.71
Permanent Ineff=
       F       F
Bank Sta=307.2,335.7
XS Rating Curve= 0 ,0
Exp/Cntr(USF)=0,0
Exp/Cntr=0.3,0.1

Type RM Length L Ch R = 1 ,3940    ,178.3,168,154.6
XS GIS Cut Line= 4
 2283121.9825305557737.2865548252283375.81717607557739.317231989
2283469.22832564557804.2989012552283629.65182164557796.176192597
#Sta/Elev= 30
       0 3942.36    34.2 3928.08    66.8 3916.73      83 3913.39   106.2 3906.95
   118.2 3906.12   130.2  3903.3   138.2 3902.81   174.2 3895.97   186.2 3892.38
   198.2 3886.18   206.2 3883.71   218.2 3882.57   250.2 3882.38   280.53877.756
   288.4 3876.35   299.1 3876.06   313.1  3877.7   321.5 3878.73   337.1  3877.7
   341.2 3878.43   351.7 3881.98   366.3 3889.24   382.6 3895.46   386.6 3896.17
   430.7 3902.91   446.7 3906.29   482.7 3907.42   498.7 3914.73   528.3 3923.39
#Mann= 5 ,-1,0
       0      .1       0   280.5    .045       0   313.1      .1       0
  343.84     .12       0  417.63      .1       0
Bank Sta=280.5,313.1
XS Rating Curve= 0 ,0
Exp/Cntr(USF)=0,0
Exp/Cntr=0.3,0.1

Type RM Length L Ch R = 1 ,3772    ,183.6,180.8,176.9
XS GIS Cut Line= 4
2283119.95185334557905.8327594822283268.19128635557911.924790976
2283475.32035713 557918.016822472283611.37572716 557918.01682247
#Sta/Elev= 30
       0 3933.75    32.3 3921.72    80.2  3905.8    92.3 3903.28   100.3 3900.25
   116.3 3898.54   148.4 3892.94   184.2 3880.06   196.4 3877.87   205.73874.676
   208.4 3873.64   220.4 3873.19   228.4  3873.3   236.4 3874.74   248.4 3875.91
   260.4 3875.52   272.4 3876.28   284.4 3874.67   304.4 3874.24   312.4 3875.09
   320.6  3877.4   344.4 3890.19   353.2 3893.27   364.4 3895.28   408.4 3900.47
   424.4 3903.55   440.4 3904.47   448.4 3903.98   460.4 3908.47   491.6 3917.39
#Mann= 6 ,-1,0
       0      .1       0     100     .12       0   205.7    .045       0
   236.4     .12       0  395.58      .1       0  491.64     .12       0
Bank Sta=205.7,236.4
XS Rating Curve= 0 ,0
Exp/Cntr(USF)=0,0
Exp/Cntr=0.3,0.1

Type RM Length L Ch R = 1 ,3591    ,94,82.5,70.3
XS GIS Cut Line= 4
2283180.87216828558121.0845389242283296.62076665558100.777767279
2283501.71916027558070.3176098112283597.16098701558072.348286975
#Sta/Elev= 30
       0 3899.48    11.5 3896.21    19.6 3892.98    35.8 3891.45    51.1 3888.67
    92.7 3885.66   104.9 3885.55   129.2 3883.02   153.5 3872.79   161.5 3870.74
   165.73870.356   177.7 3869.46   189.9 3870.38   210.1  3872.5   230.3 3869.17
   245.7  3868.9   262.6 3870.35   278.8 3869.19   282.9 3869.72   286.9 3871.29
     291 3873.89   307.1 3887.11   313.9  3890.5     321 3892.76   327.3 3894.43
   341.8 3896.41   371.3 3896.88   383.3  3901.1   411.3 3907.84   420.3 3910.66
#Mann= 5 ,-1,0
       0      .1       0  137.52     .12       0   165.7    .045       0
   189.9     .12       0  237.52      .1       0
Bank Sta=165.7,189.9
XS Rating Curve= 0 ,0
Exp/Cntr(USF)=0,0
Exp/Cntr=0.3,0.1

Type RM Length L Ch R = 1 ,3508    ,89.4,94.5,115.3
XS GIS Cut Line= 4
2283174.40426914558186.1764402042283368.46333436 558182.67988047
2283427.90484984558124.1125049292283582.62761806558114.496965661
#Sta/Elev= 30
       0 3899.89     5.8 3897.92     9.8 3897.13    21.8 3892.59    33.8 3889.15
    45.8 3888.61    57.7 3886.32    97.8 3882.44   125.8 3881.31   149.8 3879.26
   161.8 3876.99   177.8 3871.93   194.9 3871.61   206.3 3869.69   224.7 3868.84
     233 3868.89   238.6 3869.68     243  3870.3   248.7 3870.33   268.5 3869.21
   289.8 3868.73   305.9 3867.35   313.9 3868.77   322.1 3871.26   343.1  3883.1
     354 3890.56     366  3893.8     394 3895.11   414.1 3902.47   432.6 3907.86
#Mann= 7 ,-1,0
       0      .1       0      50     .12       0     150      .1       0
  204.09     .12       0   206.3    .045       0   238.6     .12       0
  264.09      .1       0
Bank Sta=206.3,238.6
XS Rating Curve= 0 ,0
Exp/Cntr(USF)=0,0
Exp/Cntr=0.3,0.1

Type RM Length L Ch R = 1 ,3414    ,117.5,116.7,119.9
XS GIS Cut Line= 4
2283190.67984171558214.417065355 2283402.2217056558209.172225754
2283515.85989695558202.1791062862283573.55313256558199.556686486
#Sta/Elev= 30
       0 3895.96    13.5  3890.9    26.1 3887.31    33.9 3886.93    45.5 3885.44
    49.5 3885.65    57.5  3884.4    69.5 3883.29    85.5 3882.58   129.5 3878.64
   143.9 3876.43   165.5 3871.33   181.6    3871   193.6 3871.66   205.6 3870.62
   241.6 3869.47   245.6  3869.2   258.7  3866.4   269.7 3864.74   277.6 3863.57
   281.7 3863.49   299.1 3864.83   301.7 3865.23   305.7 3867.66   333.8 3889.32
   337.8 3890.53   345.7  3890.9   349.8 3892.12   361.8 3897.59   383.2 3905.57
#Mann= 7 ,-1,0
       0      .1       0      30     .12       0     130      .1       0
  231.61     .12       0   269.7    .045       0   299.1     .12       0
  325.46      .1       0
Bank Sta=269.7,299.1
XS Rating Curve= 0 ,0
Exp/Cntr(USF)=0,0
Exp/Cntr=0.3,0.1

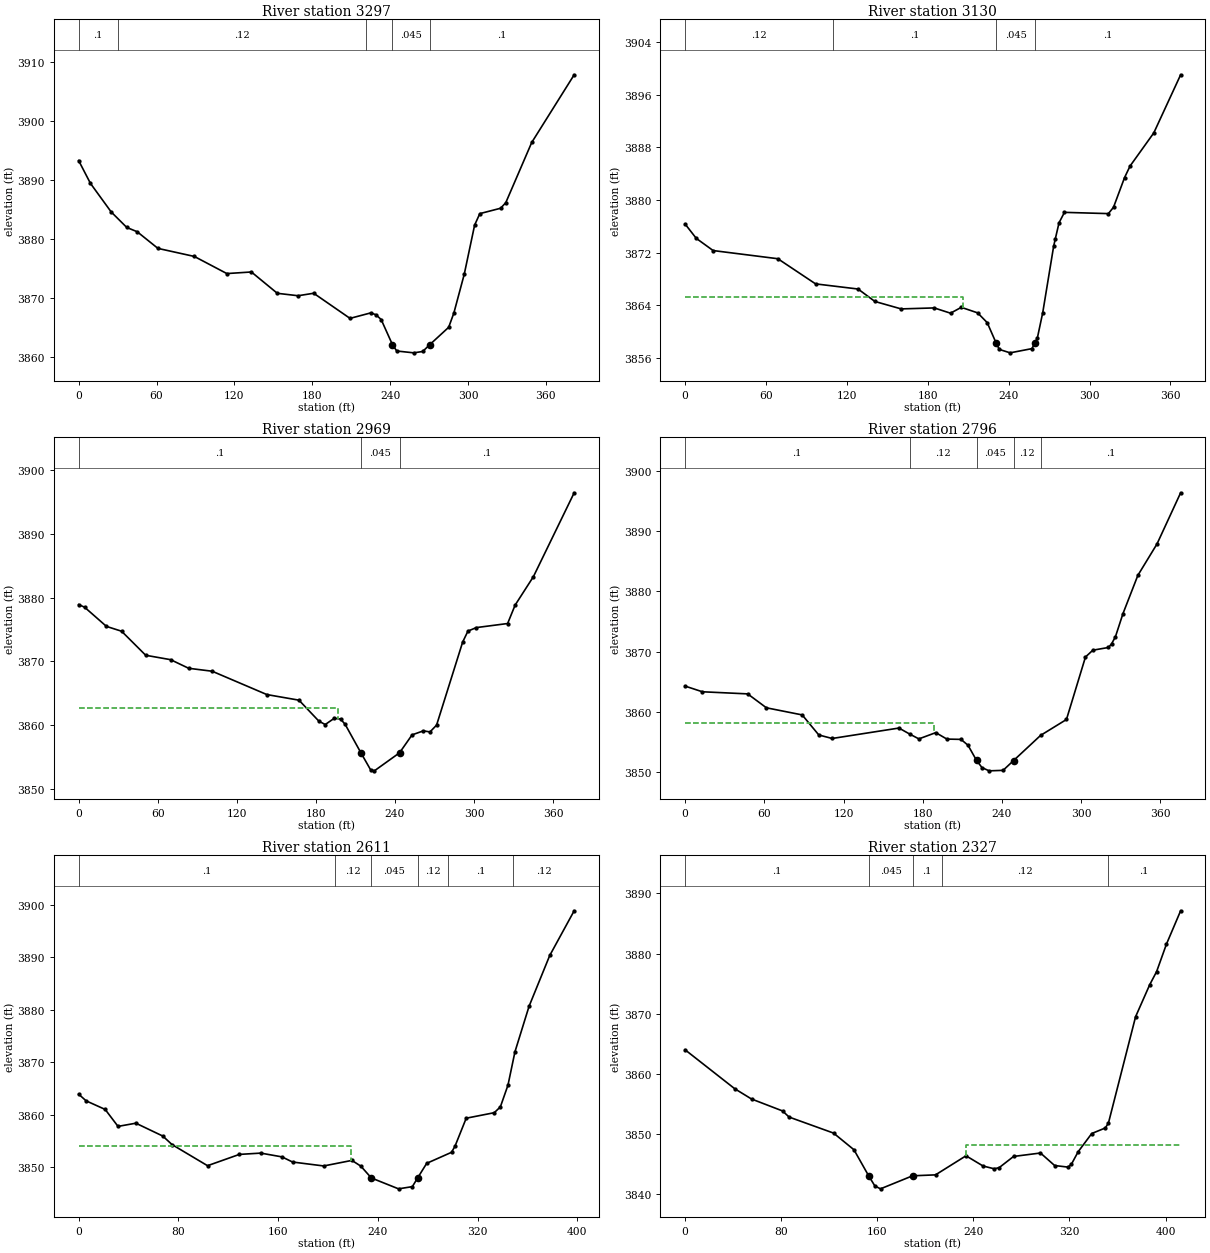
Type RM Length L Ch R = 1 ,3297    ,168.5,166.8,164.1
XS GIS Cut Line= 4
2283195.08690843 558320.090901052283396.12394772 558320.09090105
2283513.90322326 558320.090901052283576.85421536 558320.09090105
#Sta/Elev= 30
       0 3893.29     9.1 3889.43    25.1 3884.59    37.1 3881.97    45.1 3881.25
    61.1 3878.43    89.1 3877.07   114.2 3874.17   133.1 3874.44   153.1 3870.83
   169.1 3870.42   181.1 3870.84   209.1 3866.59   225.1 3867.52   229.1  3867.2
   233.1 3866.39   241.83862.141   245.1 3861.07   258.2 3860.76   265.1 3860.99
   270.43862.116   285.1 3865.08   289.1 3867.49   297.1 3874.05   305.1 3882.37
   309.1 3884.31   325.1 3885.22   329.1 3886.16   349.1 3896.35   381.8  3907.8
#Mann= 5 ,-1,0
       0      .1       0      30     .12       0  221.04      .1       0
   241.8    .045       0   270.4      .1       0
Bank Sta=241.8,270.4
XS Rating Curve= 0 ,0
Exp/Cntr(USF)=0,0
Exp/Cntr=0.3,0.1

Type RM Length L Ch R = 1 ,3130    ,170.8,161.6,150.6
XS GIS Cut Line= 4
2283215.39368007558492.6984600362283400.18530205558492.698460036
2283524.05660908558478.4837198842283580.91556969558466.299656897
#Sta/Elev= 30
       0 3876.35     8.3 3874.17    20.8 3872.32    68.8 3871.08    96.8 3867.26
   128.3 3866.48   140.8 3864.59   160.3 3863.46   184.8 3863.61   196.9 3862.81
   204.9  3863.7     217 3862.86   224.1 3861.38   230.63858.344   233.1 3857.31
   241.1 3856.79   257.3 3857.43   259.63858.348   261.3 3859.03   265.3 3862.89
   273.4 3872.98   274.6 3874.07   277.4 3876.54   281.4 3878.12     314 3877.93
   317.8 3878.89     326  3883.4   330.1 3885.16   347.7 3890.19   367.6 3899.01
#Mann= 4 ,-1,0
       0     .12       0     110      .1       0   230.6    .045       0
   259.6      .1       0
#XS Ineff= 2 , 0
          206.18 3865.24
Permanent Ineff=
       F       F
Bank Sta=230.6,259.6
XS Rating Curve= 0 ,0
Exp/Cntr(USF)=0,0
Exp/Cntr=0.3,0.1

Type RM Length L Ch R = 1 ,2969    ,173.4,172.7,170.3
XS GIS Cut Line= 4
2283292.55941233558779.0239402372283432.67613668 558677.49008201
2283546.39405789558594.2323182632283599.19166417558561.741483631
#Sta/Elev= 30
       0 3878.92     4.5 3878.51    21.1  3875.5    32.6 3874.74    50.9 3870.97
    69.8 3870.28    83.5 3868.93   101.3 3868.47   142.8 3864.81   167.2 3863.93
   182.3 3860.64   187.1 3860.11   193.9 3861.08   198.7 3860.98   202.2 3860.15
   214.13855.709   221.6 3852.99   224.4 3852.85   243.53855.678     253 3858.49
   261.6 3859.12   266.6 3858.95   271.6 3860.02   291.4 3873.05   295.4 3874.76
   301.7 3875.31   325.5 3875.95   331.2 3878.84   345.1 3883.31     376 3896.45
#Mann= 3 ,-1,0
       0      .1       0   214.1    .045       0   243.5      .1       0
#XS Ineff= 2 , 0
          196.69 3862.72
Permanent Ineff=
       F       F
Bank Sta=214.1,243.5
XS Rating Curve= 0 ,0
Exp/Cntr(USF)=0,0
Exp/Cntr=0.3,0.1

Type RM Length L Ch R = 1 ,2796    ,186.1,185.2,184.8
XS GIS Cut Line= 4
2283383.93988473558935.3860819072283526.08728625558825.729515022
2283627.62114447558736.3797197822283674.32671926558697.796853655
#Sta/Elev= 30
       0 3864.29    13.1 3863.35    47.4    3863    61.6 3860.69    88.7 3859.51
   101.3 3856.18   111.4  3855.6     162 3857.33     170 3856.35   177.1 3855.53
   189.9 3856.57   198.3  3855.5     209 3855.45   214.3 3854.48   220.83851.955
   224.9 3850.77   230.3 3850.23   240.9 3850.31   248.83851.931   269.3 3856.11
   288.9 3858.75   303.3 3869.12   308.9 3870.25   320.7  3870.7   323.1 3871.31
     326 3872.48   331.7 3876.31     343 3882.67   357.5 3887.88   375.4 3896.37
#Mann= 5 ,-1,0
       0      .1       0     170     .12       0   220.8    .045       0
   248.8     .12       0  269.53      .1       0
#XS Ineff= 2 , 0
          188.93 3858.14
Permanent Ineff=
       F       F
Bank Sta=220.8,248.8
XS Rating Curve= 0 ,0
Exp/Cntr(USF)=0,0
Exp/Cntr=0.3,0.1

Type RM Length L Ch R = 1 ,2611    ,273.9,284.2,272.1
XS GIS Cut Line= 4
2283487.50442012559097.8402550712283609.34504999559000.367751173
2283737.27771136558884.6191527932283786.01396331558835.882900844
#Sta/Elev= 30
       0 3863.92       6 3862.64    21.3    3861    31.6 3857.77    45.9 3858.38
    67.5 3855.93    74.9 3854.31   103.4 3850.28   128.9 3852.43   146.1 3852.68
   163.1 3851.96   171.6 3850.98   196.6 3850.23   219.2 3851.29   226.4 3850.19
   234.83847.942   256.6 3845.87   267.7 3846.29   271.9 3847.94   279.2 3850.73
   299.1 3852.83   301.9 3853.99   310.9 3859.33   333.4 3860.38   338.3 3861.49
   344.4 3865.63     350 3871.99   361.3 3880.65   377.9 3890.34   397.5 3898.86
#Mann= 6 ,-1,0
       0      .1       0  206.03     .12       0   234.8    .045       0
   271.9     .12       0  296.03      .1       0  348.56     .12       0
#XS Ineff= 2 , 0
          218.55 3854.11
Permanent Ineff=
       F       F
Bank Sta=234.8,271.9
XS Rating Curve= 0 ,0
Exp/Cntr(USF)=0,0
Exp/Cntr=0.3,0.1

Type RM Length L Ch R = 1 ,2327    ,218.5,219.6,219.8
XS GIS Cut Line= 4
 2283637.7745303559304.9693258542283725.09364837559231.864947931
2283853.02630974559107.9936408932283938.31475065559022.705199983
#Sta/Elev= 30
       0 3864.02    41.3 3857.56    55.3 3855.85    81.1 3853.87    86.6 3852.85
   123.6 3850.19   140.6 3847.42   152.83843.106     158 3841.41   162.7 3840.93
   189.43843.095   208.5 3843.25   233.9 3846.42   248.1 3844.72   257.4 3844.26
   261.5 3844.45   273.5 3846.31   295.9 3846.88   307.7  3844.8   318.8 3844.54
   321.6    3845   327.3  3847.1   338.6 3850.12   349.9 3851.04   352.5 3851.87
   375.1 3869.52   386.9 3874.85   392.6 3877.01   400.8 3881.58   412.6 3887.11
#Mann= 5 ,-1,0
       0      .1       0   152.8    .045       0   189.4      .1       0
  213.88     .12       0  351.96      .1       0
#XS Ineff= 2 , 0
                             234         3848.14
Permanent Ineff=
       F       F
Bank Sta=152.8,189.4
XS Rating Curve= 0 ,0
Exp/Cntr(USF)=0,0
Exp/Cntr=0.3,0.1

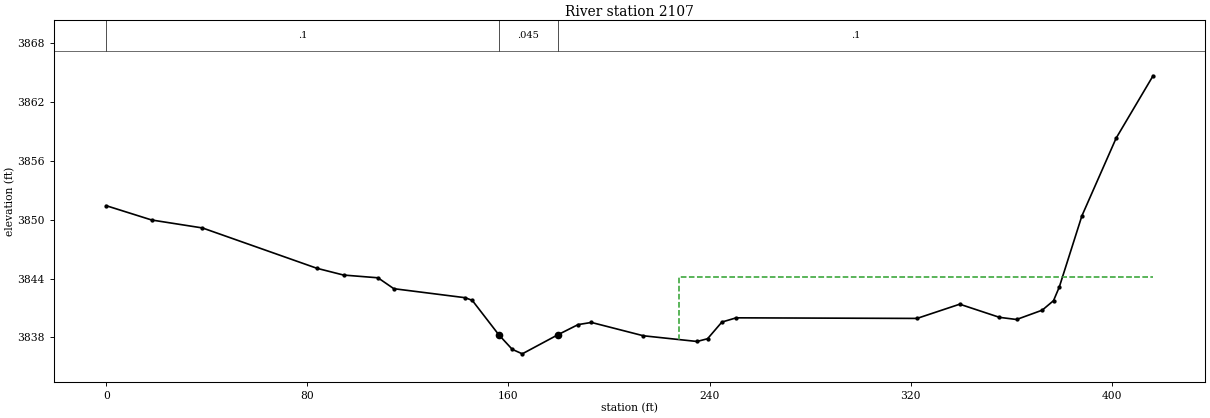
Type RM Length L Ch R = 1 ,2107    ,249.3,244.4,239.4
XS GIS Cut Line= 4
2283773.82990032 559459.300790362283863.17969556559390.257766765
2283985.02032544559286.6932313732284086.55418366559185.159373146
#Sta/Elev= 30
       0 3851.43    18.1 3849.97    38.3 3849.16    83.8 3845.05    94.4 3844.36
   108.1 3844.08   114.4 3842.97   142.8 3842.05   145.6 3841.78   156.2 3838.26
   161.5 3836.79   165.5 3836.33   179.7 3838.28   187.7 3839.31     193 3839.53
   213.7 3838.17     235 3837.59   239.2 3837.87   244.9 3839.57   250.6    3840
   322.5 3839.94   339.5 3841.39   355.3 3840.05   362.1 3839.83   372.3 3840.78
   376.8 3841.75   379.1 3843.14   388.1  3850.4   401.7 3858.31   416.4 3864.67
#Mann= 3 ,-1,0
       0      .1       0   156.2    .045       0   179.7      .1       0
#XS Ineff= 2 , 0
                          228.01         3844.19
Permanent Ineff=
       F       F
Bank Sta=156.2,179.7
XS Rating Curve= 0 ,0
Exp/Cntr(USF)=0,0
Exp/Cntr=0.3,0.1