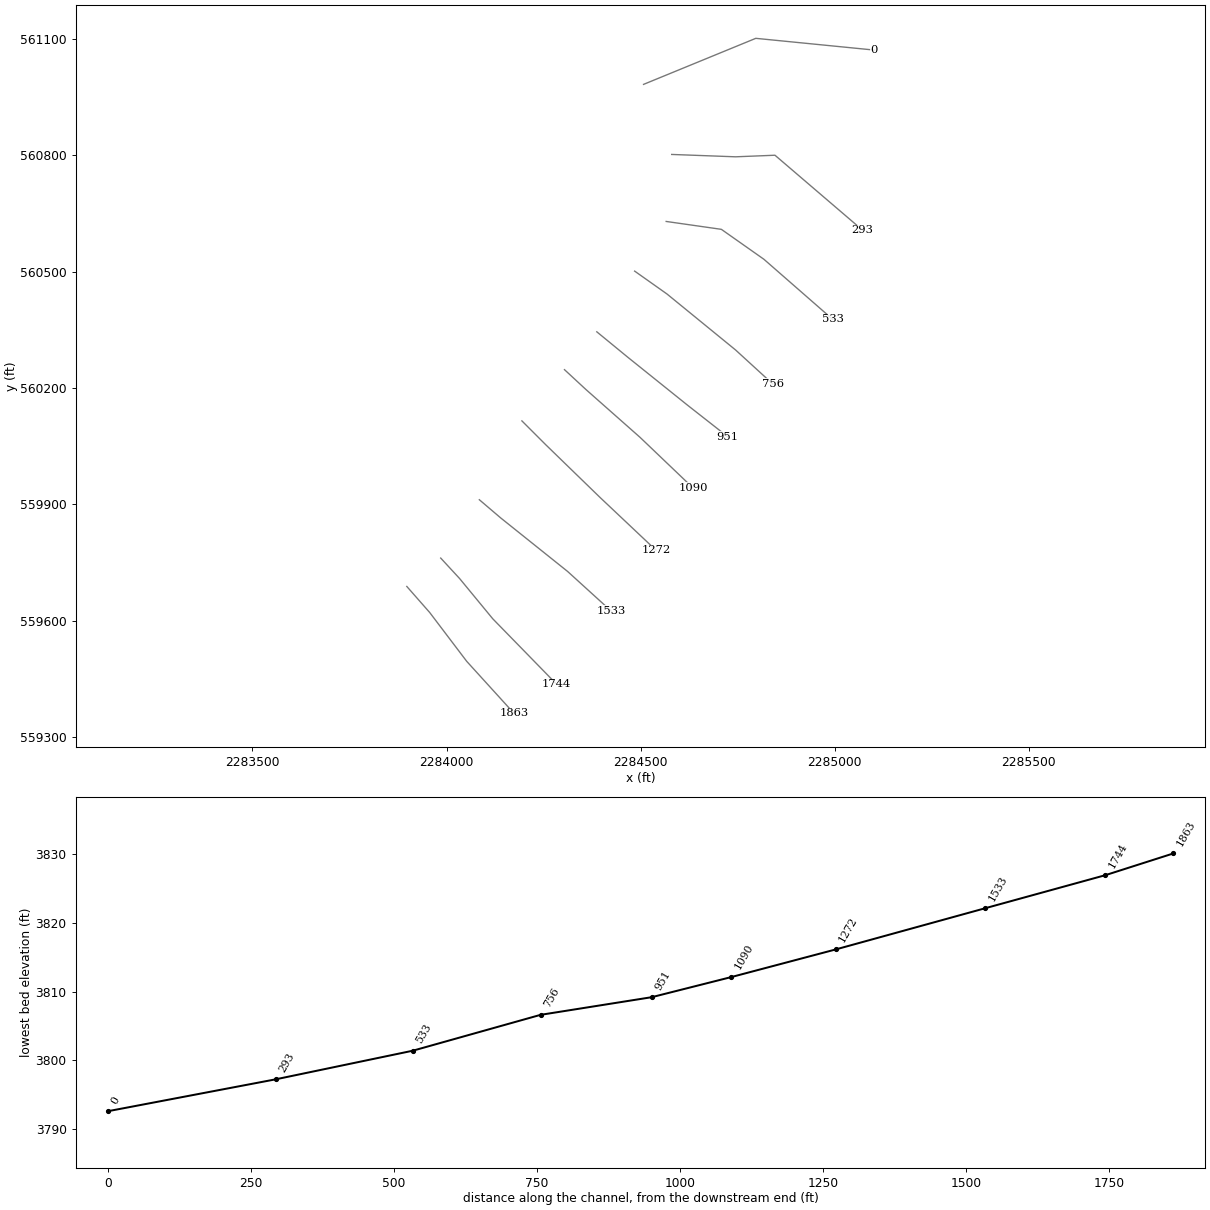
HEC-RAS study FIRSTFK.prj: FIRSTFK

--- FIRSTFK.g01 (geometry) --- (continued)

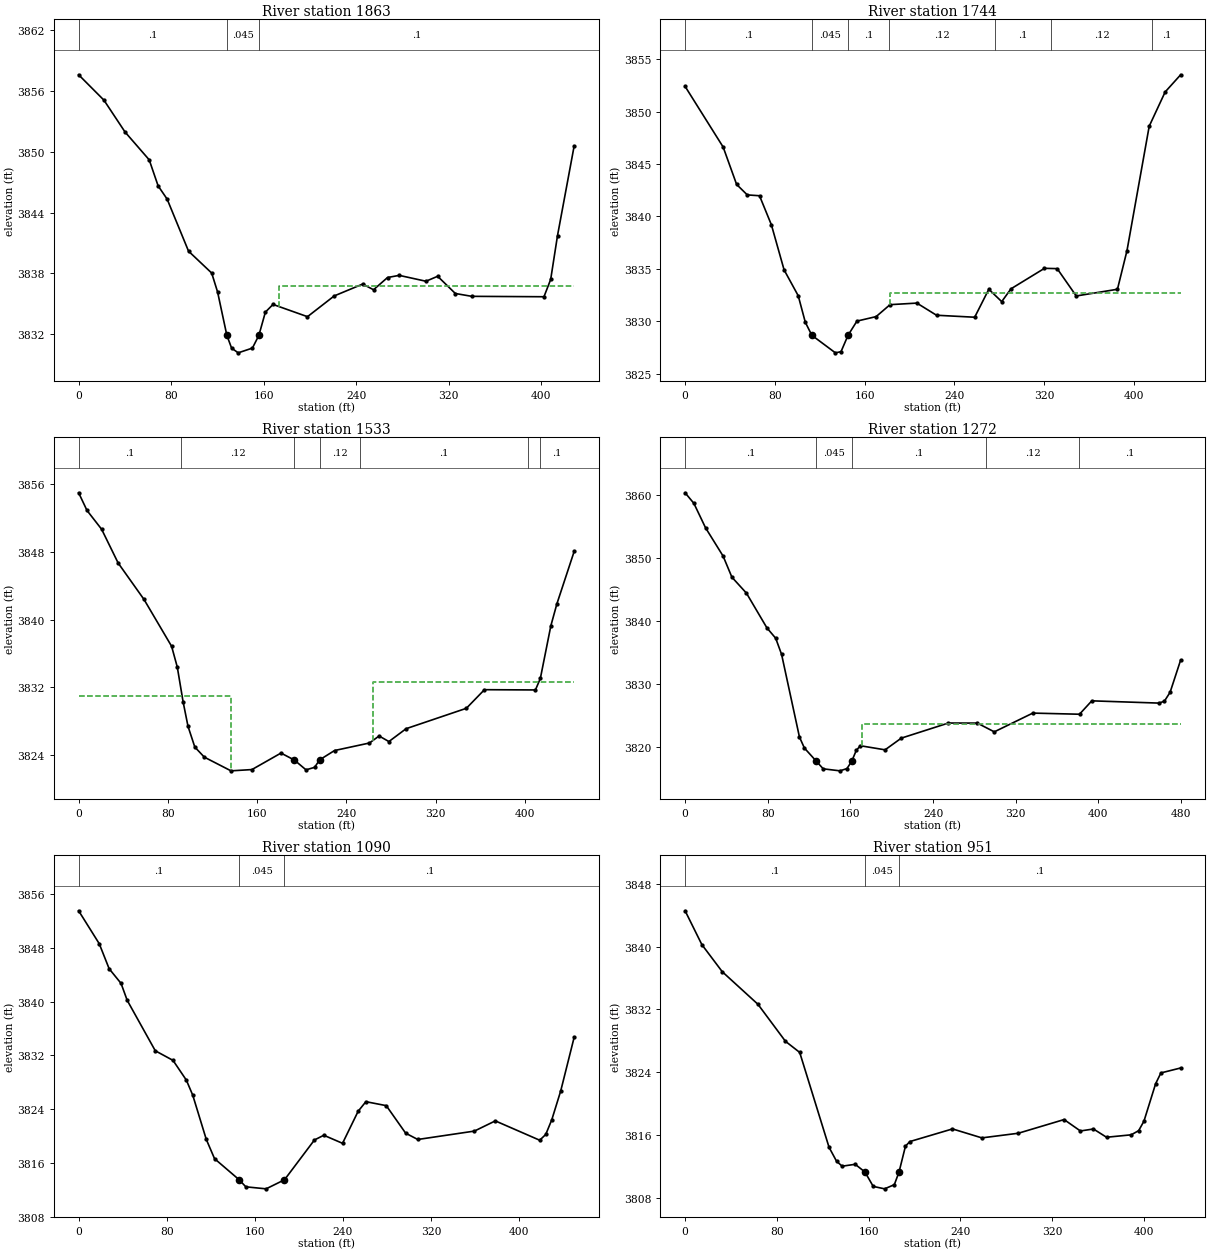
Type RM Length L Ch R = 1 ,1863    ,118.8,118.9,119.8
XS GIS Cut Line= 4
2283897.70120736559688.7673099532283956.59084513559621.754963523
2284052.03267187559495.8529793222284173.87330174559361.828286462
#Sta/Elev= 30
       0 3857.61    21.9  3855.1    40.1 3851.96      61 3849.21    68.7 3846.64
    76.5 3845.33      95 3840.19     115 3838.03   120.1 3836.16   128.13831.882
   132.2 3830.62   137.9 3830.15   150.2 3830.62   155.83831.881   161.4 3834.17
     168 3834.93   197.8 3833.72   220.9 3835.77   245.5 3836.94   254.9 3836.38
     267 3837.59   277.1  3837.8   300.2 3837.22   310.3 3837.71   325.6 3836.01
   339.8 3835.73   402.2 3835.69     408  3837.4   413.9 3841.73   428.3 3850.59
#Mann= 3 ,-1,0
       0      .1       0   128.1    .045       0   155.8      .1       0
#XS Ineff= 2 , 0
                          173.26         3836.75
Permanent Ineff=
       F       F
Bank Sta=128.1,155.8
XS Rating Curve= 0 ,0
Exp/Cntr(USF)=0,0
Exp/Cntr=0.3,0.1

Type RM Length L Ch R = 1 ,1744    ,207.6,210.5,213.5
XS GIS Cut Line= 4
2283985.02032544559761.8716878772284033.75657738559709.074081599
 2284119.0450183559605.5095462072284283.52986862 559436.96334155
#Sta/Elev= 30
       0 3852.42    33.9 3846.63    45.9 3843.06    55.4 3842.06    66.3 3841.98
    76.9  3839.2    88.2  3834.9   100.8 3832.43   107.1  3829.9   112.93828.658
   133.9 3826.98   138.9 3827.09   145.2 3828.66   153.1 3830.01   170.2 3830.44
   182.6 3831.58   206.5 3831.73     224 3830.57     258 3830.38   270.6 3833.05
   282.1 3831.87   290.3 3833.09   320.2 3835.05   331.5 3835.02   348.5 3832.41
   385.2 3833.05   393.7 3836.74   413.5 3848.62   427.7 3851.89   441.5 3853.53
#Mann= 7 ,-1,0
       0      .1       0   112.9    .045       0   145.2      .1       0
  181.85     .12       0  276.02      .1       0  326.02     .12       0
  416.02      .1       0
#XS Ineff= 2 , 0
                           182.6         3832.68
Permanent Ineff=
       F       F
Bank Sta=112.9,145.2
XS Rating Curve= 0 ,0
Exp/Cntr(USF)=0,0
Exp/Cntr=0.3,0.1

Type RM Length L Ch R = 1 ,1533    ,262.2,261,251.7
XS GIS Cut Line= 4
 2284084.5235065559912.1417980532284139.35178994559865.436223269
2284311.95934893 559727.350176082284423.64659298559625.816317852
#Sta/Elev= 30
       0 3855.01     7.5 3852.92    20.6  3850.7    35.4 3846.71    58.6  3842.4
    83.3 3836.87    88.4 3834.41    93.6 3830.31      98 3827.41   104.1 3824.96
   112.6 3823.77   136.5 3822.15   155.3  3822.3   181.3 3824.25   193.33823.425
   203.7 3822.27   211.4 3822.56     2163823.454   229.3 3824.55   260.6 3825.44
   269.2 3826.27     278 3825.61   293.4 3827.13   347.4 3829.54   363.6 3831.74
   409.3 3831.71   413.7 3833.07   423.1 3839.29   428.5 3841.88     444 3848.08
#Mann= 7 ,-1,0
       0      .1       0   92.02     .12       0   193.3    .045       0
     216     .12       0  252.02      .1       0  403.07     .12       0
  413.07      .1       0
#XS Ineff= 2 , 0
          136.96    3831  263.48         3832.59
Permanent Ineff=
       F       F
Bank Sta=193.3,216
XS Rating Curve= 0 ,0
Exp/Cntr(USF)=0,0
Exp/Cntr=0.3,0.1

Type RM Length L Ch R = 1 ,1272    ,179.7,182.6,183
XS GIS Cut Line= 4
2284194.18007338560115.2095145082284255.10038832560054.289199572
2284395.21711267559918.2338295472284539.39519136559782.178459523
#Sta/Elev= 30
       0 3860.36     8.5 3858.68    19.8 3854.79    36.8 3850.29    45.3 3846.94
    59.4  3844.4    79.2 3838.88    87.7 3837.23    93.4 3834.67   110.7 3821.52
   115.5 3819.77   126.83817.722   133.7 3816.47   149.9 3816.15   156.7 3816.51
   161.43817.704   165.7  3819.4   169.7 3820.14   193.6 3819.49   209.3 3821.35
   254.9 3823.75   282.9 3823.74   299.3 3822.35   336.6 3825.33   381.8 3825.15
   393.7 3827.28   458.8 3826.92     464 3827.23   469.5 3828.64   479.7 3833.76
#Mann= 5 ,-1,0
       0      .1       0   126.8    .045       0   161.4      .1       0
  291.46     .12       0  381.46      .1       0
#XS Ineff= 2 , 0
                           171.1         3823.67
Permanent Ineff=
       F       F
Bank Sta=126.8,161.4
XS Rating Curve= 0 ,0
Exp/Cntr(USF)=0,0
Exp/Cntr=0.3,0.1

Type RM Length L Ch R = 1 ,1090    ,138.3,139,139.7
XS GIS Cut Line= 4
2284303.83664027560247.2035302032284358.66492371 560196.43660109
2284498.78164807560072.5652940522284634.83701809559942.601955522
#Sta/Elev= 30
       0 3853.53    18.7 3848.63    27.7  3844.9    38.5 3842.72    44.1 3840.19
    69.6 3832.68    85.7 3831.25    97.8 3828.31   103.6 3826.07   115.9 3819.48
   123.4 3816.61   145.83813.465   151.8 3812.42   170.2 3812.12   186.93813.469
   214.1  3819.4   222.6  3820.1   239.6  3818.9   253.8 3823.68   260.8  3825.1
   279.3 3824.51   296.9 3820.41   307.9 3819.47   359.3 3820.72   378.3 3822.24
   418.6 3819.36   424.1 3820.22   429.6 3822.42   437.7 3826.71   449.9  3834.7
#Mann= 3 ,-1,0
       0      .1       0   145.8    .045       0   186.9      .1       0
Bank Sta=145.8,186.9
XS Rating Curve= 0 ,0
Exp/Cntr(USF)=0,0
Exp/Cntr=0.3,0.1

Type RM Length L Ch R = 1 ,951     ,193.5,194.1,193.3
XS GIS Cut Line= 4
2284387.09440402560344.6760341022284466.29081343560279.694364836
2284620.62227794560155.8230577992284724.18681333560074.595971217
#Sta/Elev= 30
       0 3844.55    14.6 3840.25    32.4  3836.8    63.5 3832.66    87.5 3827.95
    99.9 3826.54   125.5 3814.47     132 3812.71   136.9 3812.07   148.3 3812.31
   156.8 3811.33     164  3809.5   173.9 3809.19   182.4 3809.72   186.53811.329
   192.1 3814.61   195.9  3815.2   233.1 3816.81   258.7 3815.67   290.5 3816.26
   330.4    3818   344.6 3816.55     356  3816.8   367.4 3815.75   388.9 3816.06
   395.4 3816.59     400 3817.79   410.2 3822.56   414.8 3823.93     432 3824.56
#Mann= 3 ,-1,0
       0      .1       0   156.8    .045       0   186.5      .1       0
Bank Sta=156.8,186.5
XS Rating Curve= 0 ,0
Exp/Cntr(USF)=0,0
Exp/Cntr=0.3,0.1

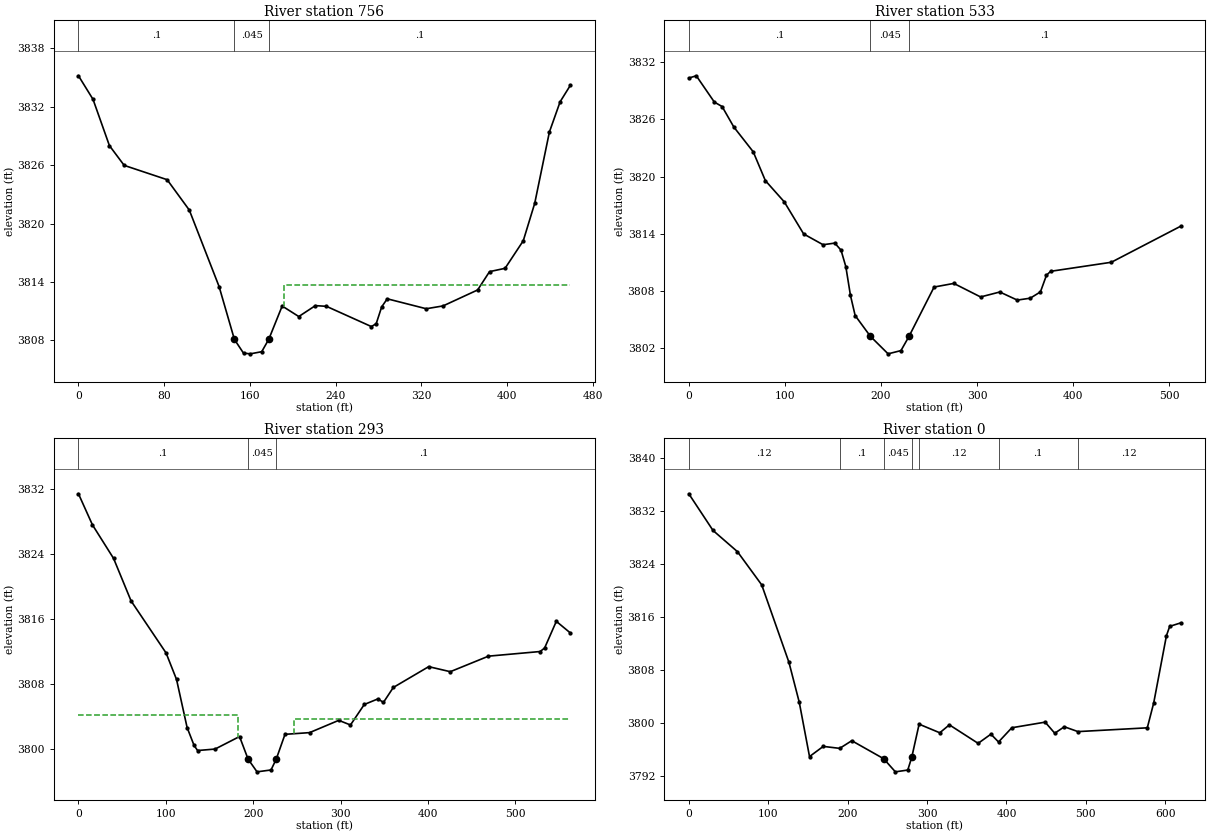
Type RM Length L Ch R = 1 ,756     ,222,223.4,225.9
XS GIS Cut Line= 4
2284484.56690791560501.0381757712284567.82467166   560442.148538
2284744.49358498560297.9704593172284839.93541171560210.651341242
#Sta/Elev= 30
       0 3835.17    13.6 3832.75    28.9    3828    42.7 3825.97    82.8  3824.5
   103.5 3821.38   131.3 3813.53   145.6  3808.1   154.1 3806.69   160.5 3806.62
   171.1 3806.84   177.73808.116   190.2 3811.53   205.7 3810.45   221.2 3811.57
   231.5  3811.5   273.5 3809.42     278 3809.72   283.1 3811.44   288.3 3812.27
   324.7 3811.25   340.4 3811.54   372.7 3813.18   383.8 3815.06   398.3  3815.4
   415.3 3818.23     426 3822.08   439.7  3829.4   449.7  3832.5459.3721 3834.21
#Mann= 3 ,-1,0
       0      .1       0   145.6    .045       0   177.7      .1       0
#XS Ineff= 2 , 0
                          191.95         3813.65
Permanent Ineff=
       F       F
Bank Sta=145.6,177.7
XS Rating Curve= 0 ,0
Exp/Cntr(USF)=0,0
Exp/Cntr=0.3,0.1

Type RM Length L Ch R = 1 ,533     ,225.3,239.6,255.6
XS GIS Cut Line= 4
 2284565.7939945560628.9708371382284707.94139601560608.664065492
 2284817.5979629 560531.498333242284994.26687621560377.166868734
#Sta/Elev= 30
       0 3830.33     7.8 3830.57    26.6 3827.81    34.7 3827.34    46.9 3825.19
    67.1 3822.59    79.7 3819.57    99.4 3817.34   119.6 3813.97   139.8 3812.84
     152 3813.01   158.5 3812.27   163.5 3810.54   168.3 3807.53   173.2 3805.41
   189.13803.226   207.5 3801.39   220.9 3801.73   229.33803.227   255.4  3808.4
   275.9 3808.78   303.8 3807.36   323.8 3807.88     342 3807.03   355.5 3807.23
   366.1 3807.89   372.4 3809.64   376.7 3810.05   439.9    3811512.2617 3814.79
#Mann= 3 ,-1,0
       0      .1       0   189.1    .045       0   229.3      .1       0
Bank Sta=189.1,229.3
XS Rating Curve= 0 ,0
Exp/Cntr(USF)=0,0
Exp/Cntr=0.3,0.1

Type RM Length L Ch R = 1 ,293     ,278.6,293.4,300.3
XS GIS Cut Line= 4
2284580.00873465560801.5783961242284744.49358498560795.486364631
 2284846.0274432 560799.547718962285071.43260847560606.633388328
#Sta/Elev= 30
       0  3831.4      16 3827.58    40.2 3823.45    60.2 3818.23   100.2 3811.84
   112.2 3808.58   124.3 3802.67   132.3 3800.46   136.3 3799.84   156.3 3800.02
   184.3 3801.56     1943798.796   204.3 3797.22   220.3 3797.45   226.33798.791
   236.3 3801.83   264.4 3802.04   297.8 3803.55   311.2 3802.98     327  3805.5
   342.7 3806.19   348.9 3805.75   360.2 3807.59   400.7 3810.15   425.4 3809.53
   469.1 3811.44   528.2 3812.01   533.3 3812.44   546.7 3815.72562.9001 3814.28
#Mann= 3 ,-1,0
       0      .1       0     194    .045       0   226.3      .1       0
#XS Ineff= 2 , 0
          182.03 3804.17   246.3         3803.76
Permanent Ineff=
       F       F
Bank Sta=194,226.3
XS Rating Curve= 0 ,0
Exp/Cntr(USF)=0,0
Exp/Cntr=0.3,0.1

Type RM Length L Ch R = 1 ,0       ,340.8,340.8,340.8
XS GIS Cut Line= 3
2284507.52755477560982.0526943672284796.64012094561100.657857331
2285102.13818859561070.384743934
#Sta/Elev= 30
       0 3834.64    30.5 3829.09    61.2 3825.89    91.8 3820.86   126.1 3809.14
   139.1 3803.09     152 3794.88   169.3 3796.42     1903796.122   205.2 3797.28
  245.31 3794.56   260.1 3792.57   275.7 3792.84  280.72 3794.77     2903799.781
     316 3798.48   328.1 3799.68   364.3 3796.88   380.4 3798.27     3903797.086
   406.7 3799.24   448.7 3800.09   460.8 3798.41   472.8 3799.39     4903798.658
   577.3 3799.23   585.4 3803.01   601.4 3813.17   605.5 3814.58   619.5 3815.11
#Mann= 7 ,-1,0
       0     .12       0     190      .1       0  245.31    .045       0
  280.72      .1       0     290     .12       0     390      .1       0
     490     .12       0
Bank Sta=245.31,280.72
XS Rating Curve= 0 ,0
Exp/Cntr=0.3,0.1
LCMann Table=0

Chan Stop Cuts=-1
Use User Specified Reach Order=0
Composite Channel Slope=5